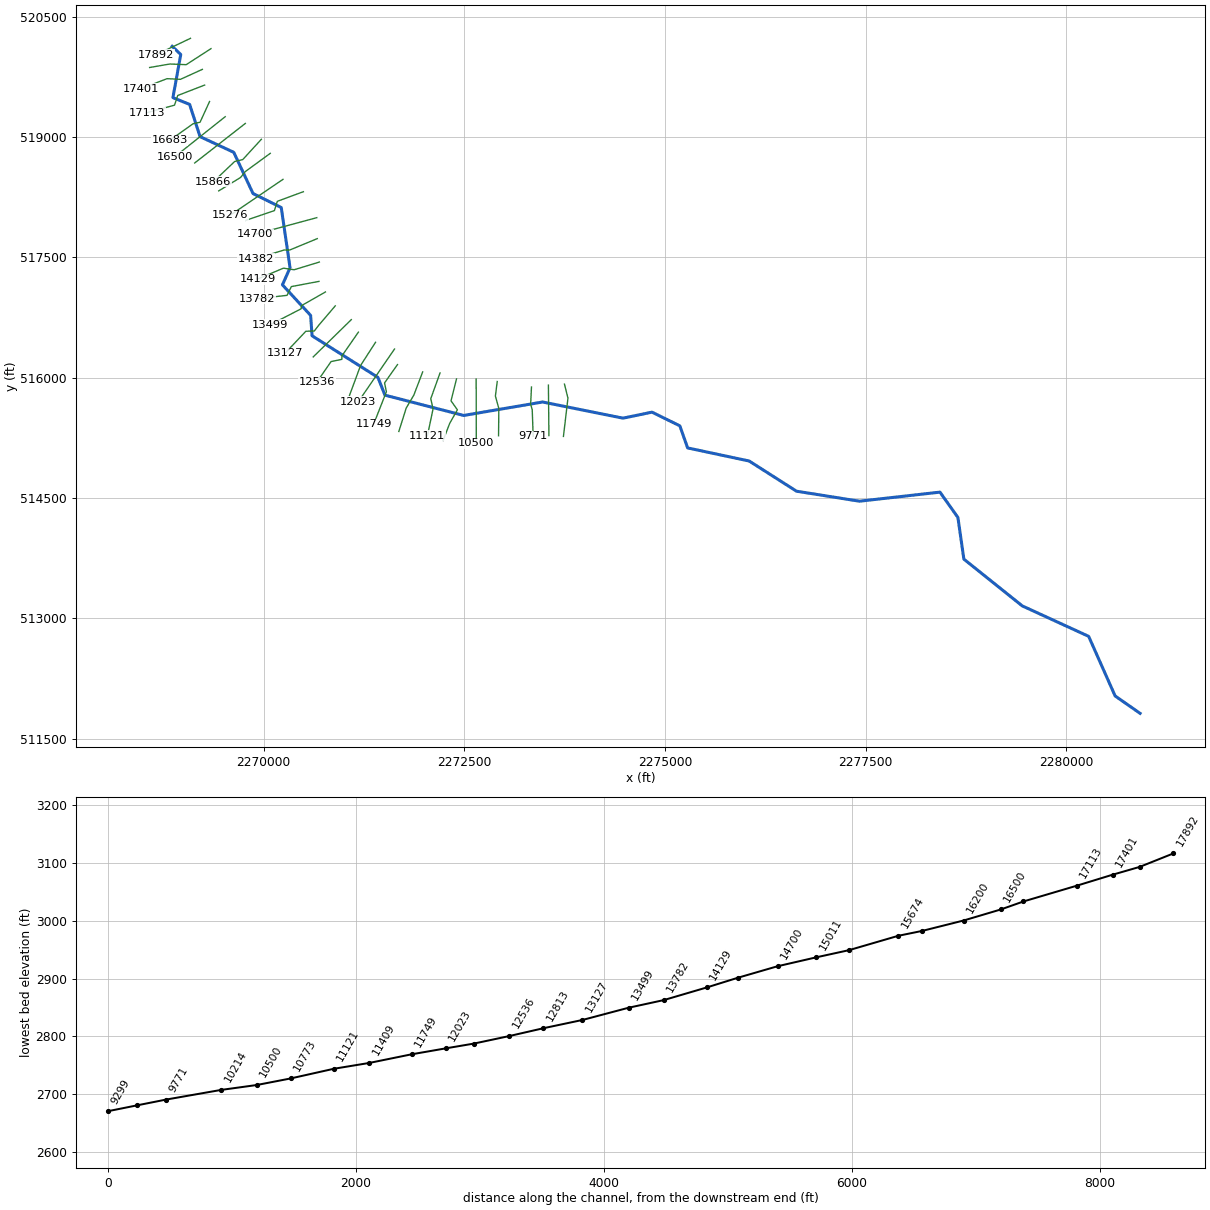
--- LTHRBRKRN.prj (project) ---

Proj Title=LTHRBRKRN
Current Plan=p01
Default Exp/Contr=0,0
English Units
Geom File=g01
Flow File=f01
Plan File=p01
Background Map Layer=Inundation Boundary (01pct Value_0)
BEGIN DESCRIPTION:
----------MODEL BY WOOD PLC 2021----------
Stream Name: Leatherbark Run
Flood Zone: Enhanced Approximate
Pocahontas County, WV
HEC-RAS Version: RAS 6.1
Vertical Datum: NAVD88
Projection: NAD 1983 StatePlane West Virginia S FIPS 4702 (US Feet)
Terrain: 1-meter LIDAR (FEMA Region III 3DEP collected 2016-2018)
Land Use: 2019 NLCD
Hydrologic Method:
WV SIR2010-5033 regression equations
Model Notes:
Normal depth tie in to Greenbrier River
END DESCRIPTION:
DSS File=dss
DSS Export Rating Curves= 0
DSS Export Rating Curve Sorted= 0
DSS Export Volume Flow Curves= 0
DXF OffsetX= 0
DXF OffsetY= 0
DXF ScaleX= 0
DXF ScaleY= 0

--- LTHRBRKRN.p01 (plan) ---

Plan Title=Floodplain
Program Version=6.10
Short Identifier=Floodplain
Geom File=g01
Flow File=f01
Subcritical Flow
K Sum by GR= 0
Std Step Tol= 0.01
Critical Tol= 0.01
Num of Std Step Trials= 20
Max Error Tol= 0.3
Flow Tol Ratio= 0.001
Split Flow NTrial= 30
Split Flow Tol= 0.02
Split Flow Ratio= 0.02
Log Output Level= 0
Friction Slope Method= 1
Unsteady Friction Slope Method= 2
Unsteady Bridges Friction Slope Method= 1
Parabolic Critical Depth
Global Vel Dist= 0 , 0 , 0
Global Log Level= 0
CheckData=False
Encroach Param=-1 ,0,0, 0
Computation Interval=0.1SEC
Output Interval=1SEC
Instantaneous Interval=Max Profile
Mapping Interval=1HOUR
Computation Time Step Use Courant=        0
Computation Time Step Use Time Series=    0
Computation Time Step Count To Double=0
Computation Time Step Max Doubling=0
Computation Time Step Max Halving=0
Computation Time Step Residence Courant=0
Run HTab= 0
Run UNet= 0
Run Sediment= 0
Run PostProcess= 0
Run WQNet= 0
Run RASMapper=-1
UNET Theta= 0
UNET Theta Warmup= 0
UNET ZTol= 0
UNET ZSATol= 0
UNET MxIter= 0
UNET Max Iter WO Improvement= 0
UNET MaxInSteps= 0
UNET DtIC= 0
UNET DtMin= 0
UNET MaxCRTS= 0
UNET WFStab= 0
UNET SFStab= 0
UNET WFX= 1
UNET SFX= 1
UNET Gravity=32.174
UNET 1D Methodology=Finite Difference
UNET DSS MLevel= 1
UNET Pardiso=0
UNET DZMax Abort= 0
UNET Use Existing IB Tables= 0
UNET Froude Reduction=False
UNET Froude Limit= 0
UNET Froude Power= 0
UNET D1 Cores= 0
UNET WindReference=Eulerian
UNET WindDragFormulation=Hsu (1988)
UNET D2 Coriolis=0
UNET D2 Cores= 0
UNET D2 Theta= 1
UNET D2 Theta Warmup= 1
UNET D2 Z Tol= 0.01
UNET D2 Volume Tol= 0.01
UNET D2 Max Iterations= 20
UNET D2 Equation= 0
UNET D2 RampUpFraction=0.1
UNET D2 TimeSlices= 1
UNET D2 Turbulence Formulation=Non-Conservative (original)
UNET D2 Eddy Viscosity=0.3
UNET D2 Transverse Eddy Viscosity=0.1
UNET D2 Smagorinsky Mixing=0
UNET D2 BCVolumeCheck=0
UNET D2 Cores=0
UNET D2 SolverType=PARDISO (Direct)
UNET D2 Minimum Iterations= 2147483647
UNET D2 Maximum Iterations= 2147483647
UNET D2 Restart Number= 10
UNET D2 Relaxation Coeff=1.3
UNET D2 SOR Precondition Iterations= 10
UNET D2 ILUT Maximum Fill= 8
UNET D2 ILUT Tolerance=1E-08
UNET D1D2 MaxIter= 0
UNET D1D2 ZTol=0.01
UNET D1D2 QTol=0.1
UNET D1D2 MinQTol=1
DSS File=dss
Write IC File= 0
Write IC File at Fixed DateTime=0
Write IC File at Sim End=0
Echo Input=False
Echo Parameters=False
Echo Output=False
Write Detailed= 0
HDF Write Warmup=0
HDF Write Time Slices=0
HDF Flush=0
HDF Compression= 1
HDF Chunk Size= 1
HDF Spatial Parts= 1
HDF Use Max Rows=0
HDF Fixed Rows= 1
Calibration Method= 0
Calibration Iterations= 20
Calibration Max Change=0.05
Calibration Tolerance=0.2
Calibration Maximum=1.5
Calibration Minimum=0.5
Calibration Optimization Method= 1
WQ AD Non Conservative
WQ ULTIMATE=-1
WQ Max Comp Step=1HOUR
WQ Output Interval=15MIN
WQ Output Selected Increments= 0
WQ Output face flow=0
WQ Output face velocity=0
WQ Output face area=0
WQ Output face dispersion=0
WQ Output cell volume=0
WQ Output cell surface area=0
WQ Output cell continuity=0
WQ Output cumulative cell continuity=0
WQ Output face conc=0
WQ Output face dconc_dx=0
WQ Output face courant=0
WQ Output face peclet=0
WQ Output face adv mass=0
WQ Output face disp mass=0
WQ Output cell mass=0
WQ Output cell source sink temp=0
WQ Output nsm pathways=0
WQ Output nsm derived pathways=0
WQ Create Restart=0
WQ Fixed Restart=0
WQ System Summary=0
WQ Write To DSS=0
Sorting and Armoring Iterations= 10
XS Update Threshold= 0.02
Bed Roughness Predictor= 0
Hydraulics Update Threshold= 0.02
Energy Slope Method= 1
Volume Change Method= 1
Sediment Retention Method= 0
Sediment TS Multiplier= 1
Warm Up Method= 0
XS Weighting Method= 0
Number of US Weighted Cross Sections= 1
Number of DS Weighted Cross Sections= 1
Upstream XS Weight=0
Main XS Weight=1
Downstream XS Weight=0
Number of DS XS's Weighted with US Boundary= 1
Upstream Boundary Weight= 1
Weight of XSs Associated with US Boundary= 0
Number of US XS's Weighted with DS Boundary= 1
Downstream Boundary Weight= 0.5
Weight of XSs Associated with DS Boundary= 0.5
Percentile Method= 0
Sediment Output Level= 3
Mass or Volume Output= 0
Output Increment Type= 1
Profile and TS Output Increment= 1
Transport Output Increment 1
XS Output Flag= 0
XS Output Increment= 10
Read HDF5 Sediment Hotstart= 0
Sediment Hotstart Type= 0
Write Gradation File= 0
Read Gradation Hotstart= 0
Write HDF5 File= 1
Write Binary Output= 1
Write DSS Sediment File= 0
DSS Sediment Output Type= 1
SV Curve= 0
Specific Gage Flag= 0
Subcell Erosion Methods= 0
Subcell Deposition Methods= 0
Advection Scheme= 1
Matrix Solver= 0
Implicit Weighting Factor= 1
Maximum Outer Loop Convergence Iterations= 5
Convergence Maximum Absolute= 0.001
Convergence RMSE= 0.0001
Grain Fractions Max Abs Error= 0.001
Max Subgrid Regions= 1
Max Subgrid Length Scale= 3.402823E+38
Initial Layer Thickness= 3.402823E+38
Min Layer Thickness= 3.402823E+38
Max Layer Thickness= 3.402823E+38
Number of Layers= 5

--- LTHRBRKRN.f01 (steady flow) ---

Flow Title=Flow
Program Version=4.00
Number of Profiles=6
Profile Names=01pct,10pct,04pct,02pct,0_2pct,01plus
River Rch & RM=LTHRBRKRN,Main,17892
     618     328     435     524     862     914
River Rch & RM=LTHRBRKRN,Main,14700
     714     380     504     606     993    1060
River Rch & RM=LTHRBRKRN,Main,12536
     878     472     623     746    1220    1300
River Rch & RM=LTHRBRKRN,Main,8994
     999     539     710     850    1380    1480
River Rch & RM=LTHRBRKRN,Main,5027
    1120     606     796     951    1540    1650
River Rch & RM=LTHRBRKRN,Main,4602
    1360     741     970    1160    1860    2010
Boundary for River Rch & Prof#=LTHRBRKRN,Main      ,1
Up Type=0
Dn Type=3
Dn Slope=0.027265
Boundary for River Rch & Prof#=LTHRBRKRN,Main      ,2
Up Type=0
Dn Type=3
Dn Slope=0.027265
Boundary for River Rch & Prof#=LTHRBRKRN,Main      ,3
Up Type=0
Dn Type=3
Dn Slope=0.027265
Boundary for River Rch & Prof#=LTHRBRKRN,Main      ,4
Up Type=0
Dn Type=3
Dn Slope=0.027265
Boundary for River Rch & Prof#=LTHRBRKRN,Main      ,5
Up Type=0
Dn Type=3
Dn Slope=0.027265
Boundary for River Rch & Prof#=LTHRBRKRN,Main      ,6
Up Type=0
Dn Type=3
Dn Slope=0.027265

--- LTHRBRKRN.g01 (geometry) ---

Geom Title=Geometry
Program Version=6.10

River Reach=LTHRBRKRN       ,Main
Reach XY= 30
     2268860.815      520130.366      2268968.28      520028.292
     2268870.491      519490.8322269078.95682009519405.708931403
      2269208.44      519004.387     2269628.433      518808.829
     2269868.026       518295.41     2270220.022      518120.507
     2270329.469      517369.578     2270234.708       517157.06
      2270585.95      516776.048      2270604.05       516521.82
      2271424.58      516003.132     2271511.881      515781.802
     2272492.304      515528.921     2273476.844      515696.508
     2274477.201      515494.901     2274838.622      515570.007
      2275185.45      515399.273     2275282.218      515124.119
      2276049.26      514960.807     2276638.883      514584.578
     2277422.815      514459.981     2278425.895      514572.968
      2278649.36       514257.21     2278723.621      513737.478
     2279450.562      513155.291     2280277.907      512775.555
     2280607.679      512032.493     2280919.018      511815.208

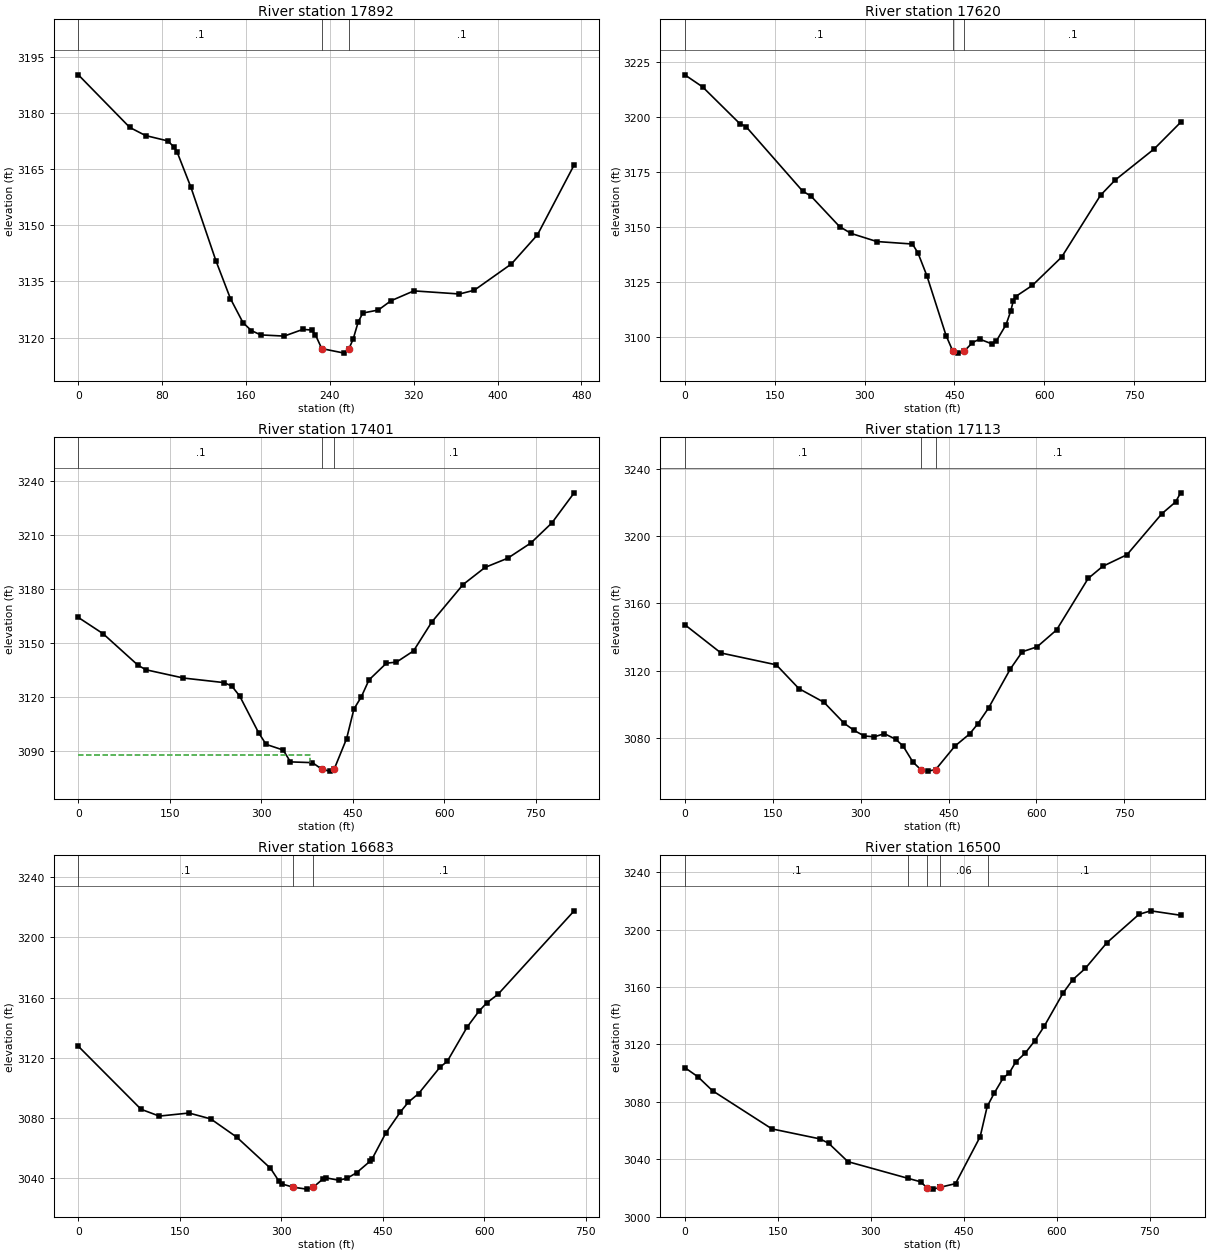
Type RM Length L Ch R = 1 ,17892   ,272.2,272.2,272.2
XS GIS Cut Line= 2
2269089.13499738520229.7052591982268662.21066257520026.111172526
#Sta/Elev= 30
       0 3190.21    49.1 3176.15    64.1 3173.99    85.3 3172.56    91.1 3170.98
    94.1 3169.68   107.4 3160.17   131.3  3140.5   145.1 3130.42   157.1 3123.99
     165  3121.9   173.9 3120.73   196.4 3120.41   214.2  3122.2   222.6 3122.03
   226.2 3120.73   232.2 3117.07   253.7 3115.86   258.1    3117   262.2 3119.63
     267  3124.2   271.4 3126.57   286.2 3127.38   298.2 3129.84   320.1 3132.49
   363.6 3131.66   377.7 3132.66   413.2  3139.7     438 3147.48     473 3166.14
#Mann= 3 ,-1,0
       0      .1       0   232.2    .045       0   258.1      .1       0
Bank Sta=232.2,258.1
XS Rating Curve= 0 ,0
Exp/Cntr(USF)=0,0
Exp/Cntr=0.3,0.1

Type RM Length L Ch R = 1 ,17620   ,218.8,218.8,218.8
XS GIS Cut Line= 4
2269345.10274166520101.4950583362269036.15898503519901.461731706
2268832.56489836519909.7716944272268580.50998843519866.127427376
#Sta/Elev= 30
       0 3219.37    29.7 3213.87    91.6 3197.18   102.1  3195.8   196.5 3166.46
   210.8 3164.07   258.4 3150.21   277.5 3147.13   320.4 3143.43     380 3142.29
   389.2 3138.23   404.1 3127.81   436.1  3100.6   447.6 3093.34   456.1 3092.59
  466.28 3093.45   480.1 3097.37   492.1 3098.98   512.2 3096.84   520.2 3098.19
   536.2 3105.56   544.2 3111.86   548.2 3116.34   552.2 3118.36   580.3 3123.48
     629 3136.34     694 3164.54   718.4 3171.45   783.3 3185.57   827.6 3197.72
#Mann= 3 ,-1,0
       0      .1       0   447.6    .045       0  466.28      .1       0
Bank Sta=447.6,466.28
XS Rating Curve= 0 ,0
Exp/Cntr(USF)=0,0
Exp/Cntr=0.3,0.1

Type RM Length L Ch R = 1 ,17401   ,288.6,288.6,288.6
XS GIS Cut Line= 4
2269237.12630414519842.9703655942268964.48555656519718.642551837
2268797.24755679519726.9525145582268474.14822852519602.420046263
#Sta/Elev= 30
       0 3164.35    40.6 3155.33    97.8 3137.86   110.8 3135.33   172.5 3130.73
   238.4 3128.22   251.6 3126.36   264.8 3120.69   295.6 3100.47     308 3093.93
     336 3090.79     348 3084.21   384.1 3083.78   400.1 3079.99   412.1 3079.08
   419.5    3080   440.1  3097.1   452.1 3113.54   464.2 3120.26   476.8 3129.68
   505.4 3138.97   521.9 3139.56   549.9 3145.78   579.7 3161.75   631.1 3182.59
   667.3 3192.13   704.5 3197.23   742.6 3205.73   776.9 3216.82   813.4  3233.5
#Mann= 3 ,-1,0
       0      .1       0   400.1    .045       0   419.5      .1       0
#XS Ineff= 2 , 0
          379.72  3088.1
Permanent Ineff=
       F       F
Bank Sta=400.1,419.5
XS Rating Curve= 0 ,0
Exp/Cntr(USF)=0,0
Exp/Cntr=0.3,0.1

Type RM Length L Ch R = 1 ,17113   ,429.9,429.9,429.9
XS GIS Cut Line= 4
2269265.71455603519647.1743538892268930.20696033519517.125955845
2268890.73463741519396.6314963862268543.89100117519302.252977852
#Sta/Elev= 30
       0 3147.31    61.7 3130.46   156.1 3123.42   194.7 3109.26   237.6 3101.09
   271.9 3088.63   289.1 3084.34   306.2 3081.07   323.4 3080.56   340.6 3082.44
   359.8 3079.13   372.4 3075.13   389.2 3065.57   402.6 3061.08   414.5 3060.14
     428 3061.03   460.8    3075     486 3082.27   499.8 3088.19   518.3 3097.69
   555.6 3120.99   575.9 3131.19   601.2 3134.13   634.4 3144.18   688.3 3174.82
   713.1 3182.02   754.6 3188.96   814.1 3213.37   837.5 3220.35   846.1 3225.79
#Mann= 3 ,-1,0
       0      .1       0   402.6    .045       0     428      .1       0
Bank Sta=402.6,428
XS Rating Curve= 0 ,0
Exp/Cntr(USF)=0,0
Exp/Cntr=0.3,0.1

Type RM Length L Ch R = 1 ,16683   ,182.9,182.9,182.9
XS GIS Cut Line= 4
2269326.77024662519441.924503295 2269208.5907115519183.688701652
 2269123.4135936 519166.03003087 2268828.3957633518956.548653535
#Sta/Elev= 30
       0  3127.7    92.7  3085.9   119.6 3081.39   163.6 3083.42   195.7 3079.52
     234 3067.46     284 3046.76   296.6 3038.16   300.8 3036.39   317.4 3034.23
   337.5 3032.94   347.4 3034.27     362 3039.88   366.1 3040.42   384.8 3038.86
   396.9 3040.08   411.2 3043.79   431.3  3051.5   434.2 3052.99   454.2 3069.97
   476.1 3084.21   487.8 3090.65     503 3096.37   534.6 3113.87   545.2 3117.67
   574.7  3140.5   591.9 3150.86   603.4 3156.37   620.6 3162.34   732.8 3217.55
#Mann= 3 ,-1,0
       0      .1       0   317.4    .045       0   347.4      .1       0
Bank Sta=317.4,347.4
XS Rating Curve= 0 ,0
Exp/Cntr(USF)=0,0
Exp/Cntr=0.3,0.1

Type RM Length L Ch R = 1 ,16500   ,300,300,300
XS GIS Cut Line= 2
 2269521.9621274519252.9953921362268895.74256084 518755.15098426
#Sta/Elev= 30
       0 3103.81    21.1 3097.43    44.7  3087.7   140.6 3061.09   218.2 3054.12
   232.2 3051.05   263.2 3038.26     360 3026.66   380.4 3024.24   390.6 3020.12
   400.9 3019.12   411.1 3020.31   411.1 3020.32   436.8 3022.94   476.6  3055.7
   487.9 3076.73   499.3 3086.04   513.9 3096.71   523.5 3100.02   533.7 3107.55
   549.1 3113.86   564.8 3122.55   579.7 3132.47   610.3 3155.73   625.7 3164.95
   646.1  3172.9     681 3190.83   732.8 3210.61   751.7 3213.07     800 3209.97
#Mann= 5 ,-1,0
       0      .1       0     360     .06       0   390.6    .045       0
   411.1     .06       0     490      .1       0
Bank Sta=390.6,411.1
XS Rating Curve= 0 ,0
Exp/Cntr(USF)=0,0
Exp/Cntr=0.3,0.1

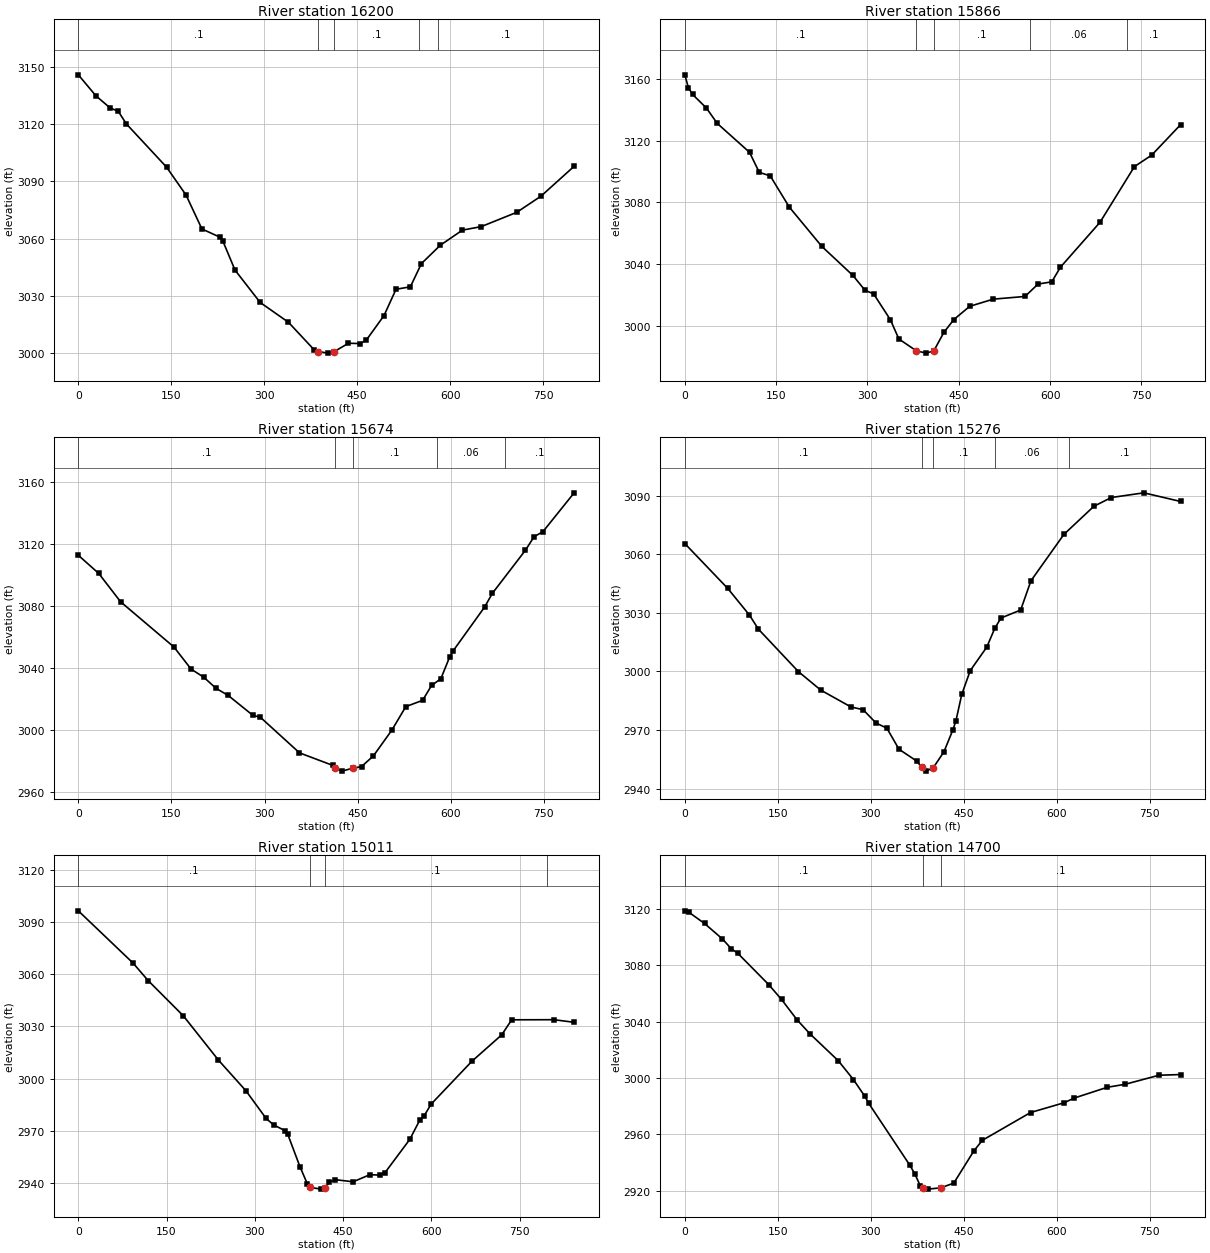
Type RM Length L Ch R = 1 ,16200   ,334.1,334.1,334.1
XS GIS Cut Line= 2
2269772.37091349 519168.896939992269142.08555174518676.210058937
#Sta/Elev= 30
       0  3145.8    28.4  3134.8      51 3128.54    64.5 3126.66    77.5 3120.11
   142.4 3097.44   173.8 3082.84   199.4 3065.08   228.7 3060.75   233.4 3058.59
   252.8 3043.54   293.4 3026.59     339 3016.22     381 3001.62   387.5  3000.9
   402.2 3000.06   413.1  3000.9   435.9 3005.24   454.2 3005.07   464.4 3006.78
   493.2 3019.72   512.6 3033.51   535.7 3034.78   553.6 3046.97   584.1 3056.57
   619.7 3064.47   650.1 3066.31   707.5 3073.81   746.6 3082.29     800 3097.92
#Mann= 5 ,-1,0
       0      .1       0   387.5    .045       0   413.1      .1       0
     550     .06       0     580      .1       0
Bank Sta=387.5,413.1
XS Rating Curve= 0 ,0
Exp/Cntr(USF)=0,0
Exp/Cntr=0.3,0.1

Type RM Length L Ch R = 1 ,15866   ,191.6,191.6,191.6
XS GIS Cut Line= 4
 2269972.1487818518971.3585355092269740.42832566518718.330789258
2269639.67002767518694.4396464352269373.20900107  518441.0085199
#Sta/Elev= 30
       0 3162.96     5.9 3154.62    12.8 3150.19    35.5 3141.38    53.3  3131.4
   106.3 3112.61   122.3  3099.6   140.3 3097.29   171.7 3076.98     225 3051.49
   276.1  3032.6   296.1 3022.91   310.1 3020.64   337.6 3003.85   351.6 2991.31
   380.4 2983.58   396.8 2982.11   409.1 2983.62   425.6 2995.63     442 3003.95
     468 3012.53   506.7 3017.19   558.8 3018.94   580.2 3026.99   602.8 3028.44
   616.9 3037.91     682 3067.13   738.5 3103.32   766.9 3110.78   814.4 3130.58
#Mann= 5 ,-1,0
       0      .1       0   380.4    .045       0   409.1      .1       0
  566.65     .06       0  726.65      .1       0
Bank Sta=380.4,409.1
XS Rating Curve= 0 ,0
Exp/Cntr(USF)=0,0
Exp/Cntr=0.3,0.1

Type RM Length L Ch R = 1 ,15674   ,398,398,398
XS GIS Cut Line= 4
2270083.10355275518796.1673537132269769.06577925518566.392566001
2269715.05102156 518496.796628212269441.33303288518328.074911948
#Sta/Elev= 30
       0  3112.6    32.9 3100.92    68.1 3082.68   154.1 3053.55   181.7 3039.36
   201.9  3034.2   221.8 3027.04   241.5 3022.41   281.2 3009.64   293.3 3008.39
   356.3 2985.49   410.1  2977.4   413.6 2975.81   424.8 2973.74   442.8 2975.71
   456.2 2976.64   475.4 2983.55   505.2 3000.17   527.6 3015.25   554.6 3019.26
   569.1 3028.86     584 3033.14   598.2 3047.15     604  3051.2   654.5 3079.29
   667.1 3088.16   720.3 3115.84   734.3 3124.59   748.4 3127.74   798.8 3152.78
#Mann= 5 ,-1,0
       0      .1       0   413.6    .045       0   442.8      .1       0
  577.22     .06       0  687.22      .1       0
Bank Sta=413.6,442.8
XS Rating Curve= 0 ,0
Exp/Cntr(USF)=0,0
Exp/Cntr=0.3,0.1

Type RM Length L Ch R = 1 ,15276   ,265.4,265.4,265.4
XS GIS Cut Line= 2
2270241.98199398518472.209591998 2269580.4617531518022.330751742
#Sta/Elev= 30
       0 3065.42    69.4 3042.41   104.3 3028.81   118.7 3021.61   183.2 2999.89
   219.4 2990.39   268.2 2981.75   287.6 2980.39   308.7 2973.51     326 2970.92
   345.6 2960.12   374.7 2953.96   382.4 2950.78   389.2 2948.92   400.8 2950.61
   418.1 2958.81   432.7 2970.17   437.5 2974.74   446.9 2988.24   460.6 3000.39
   487.2 3012.39   500.4  3022.2   510.2 3027.32   541.9 3031.38   558.5 3046.36
   611.7 3070.11     660 3084.48   688.2 3088.98   740.6 3091.38     800 3086.95
#Mann= 5 ,-1,0
       0      .1       0   382.4    .045       0   400.8      .1       0
     500     .06       0     620      .1       0
Bank Sta=382.4,400.8
XS Rating Curve= 0 ,0
Exp/Cntr(USF)=0,0
Exp/Cntr=0.3,0.1

Type RM Length L Ch R = 1 ,15011   ,311,311,311
XS GIS Cut Line= 4
2270495.59001599518318.0870679392270170.46889649518197.919373836
2270135.15155493518082.6186410782269779.69044044 517961.03273352
#Sta/Elev= 30
       0 3096.29    93.2 3066.23   118.6 3056.27   178.5 3035.99   238.2 3010.56
   285.1 2992.89   319.2 2977.07     332 2973.38   351.6    2970   355.8 2968.17
   376.7 2949.41   389.2 2939.59   393.4 2937.49   413.1 2936.48   419.5 2937.37
   426.9 2940.35   436.4 2941.92   467.2  2940.7   495.7 2944.78   512.6 2944.53
   521.1 2945.84   563.4    2965   580.3 2976.01   587.2 2978.21   599.8  2985.3
     669 3009.89   719.8 3025.08   736.7 3033.71   808.6 3033.77   842.9 3032.27
#Mann= 4 ,-1,0
       0      .1       0   393.4    .045       0   419.5      .1       0
  797.21     .06       0
Bank Sta=393.4,419.5
XS Rating Curve= 0 ,0
Exp/Cntr(USF)=0,0
Exp/Cntr=0.3,0.1

Type RM Length L Ch R = 1 ,14700   ,318.1,318.1,318.1
XS GIS Cut Line= 2
2270662.83951244517994.2671237632269890.47838617517785.800602148
#Sta/Elev= 30
       0 3118.81     6.9  3117.7    31.8 3109.82    60.8 3098.81    74.8 3091.97
    85.6  3088.6   135.3 3066.44   156.1 3055.85   180.9 3041.52   201.6 3031.59
   247.8 3012.27   272.1 2998.92   290.2 2987.26   296.9 2981.97   363.2 2938.07
   371.5 2931.64   379.8 2923.67   383.9  2921.9   392.2 2921.15   412.9 2922.07
     434 2925.42   466.3 2948.22     480  2955.8   557.9 2975.56   611.8 2982.47
   628.4 2985.84   681.7 2993.49   710.3 2995.59   765.1 3002.04     800 3002.53
#Mann= 3 ,-1,0
       0      .1       0   383.9    .045       0   412.9      .1       0
Bank Sta=383.9,412.9
XS Rating Curve= 0 ,0
Exp/Cntr(USF)=0,0
Exp/Cntr=0.3,0.1

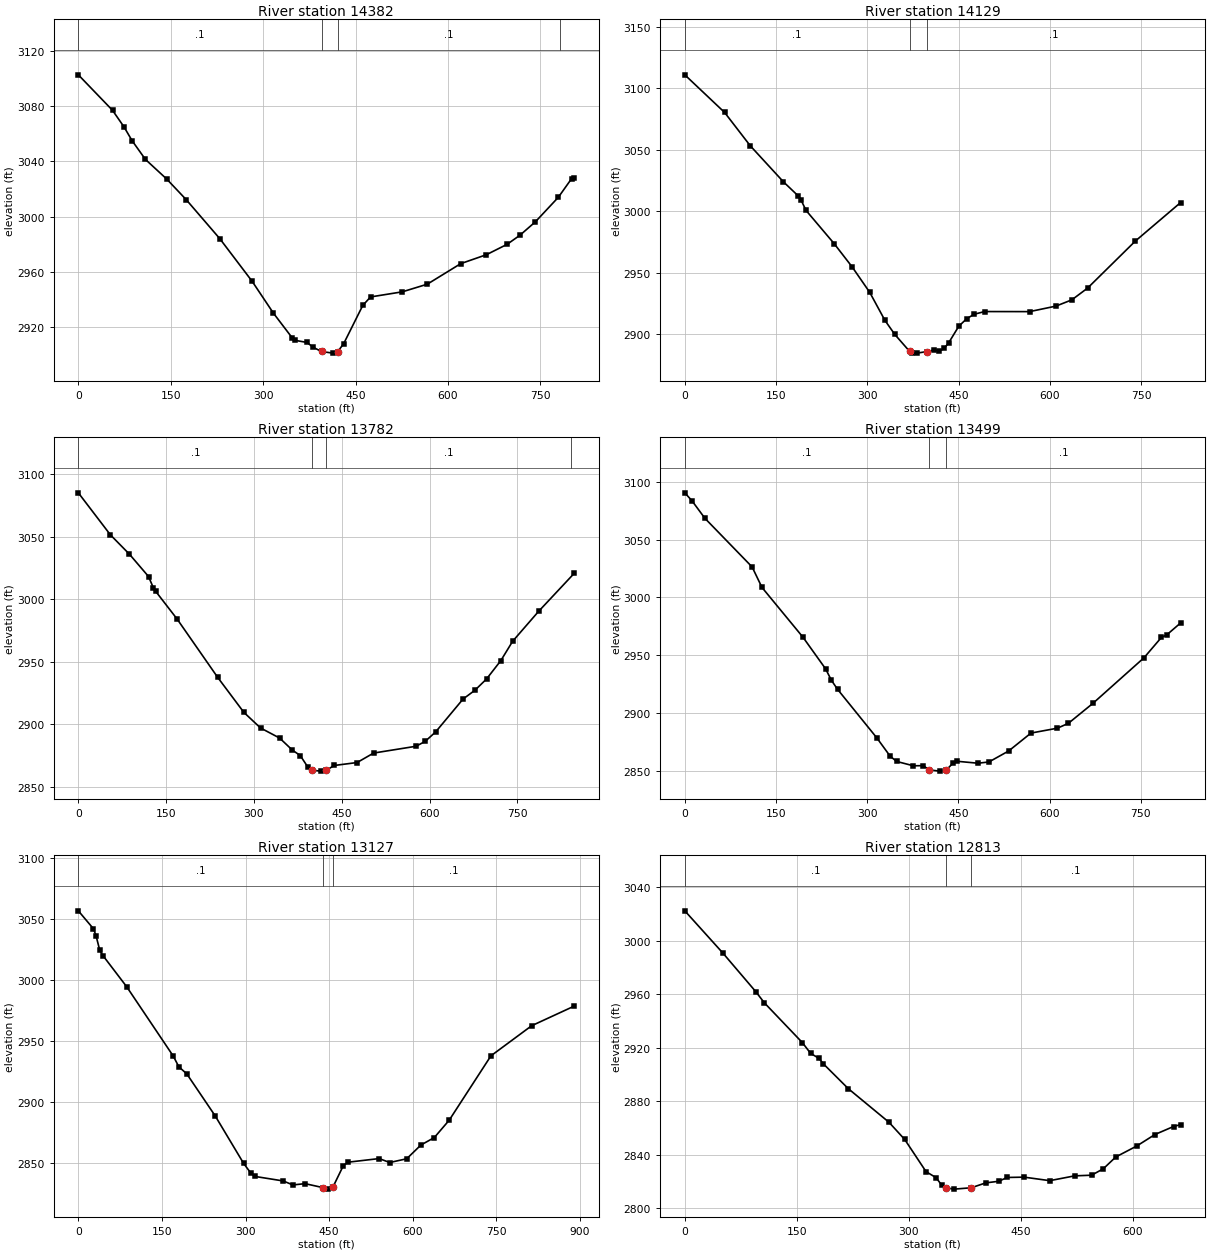
Type RM Length L Ch R = 1 ,14382   ,252.5,252.5,252.5
XS GIS Cut Line= 4
2270668.75633084517733.0789202012270325.83328158517591.010691585
2270255.19859845517591.0106915852269908.13163239517485.187677707
#Sta/Elev= 30
       0 3102.54    55.5 3076.88    74.2 3064.86    87.2 3054.97   108.9  3041.4
   143.5 3027.19   174.9 3012.41   229.7 2984.07   282.1  2953.3   316.7 2930.24
     347 2912.51   351.3 2910.69   371.2 2909.12   380.8 2905.68   394.7  2902.6
   412.8 2901.41   420.8 2902.37   430.7  2908.3   461.7 2935.93   474.3 2942.02
   525.8 2945.71   566.3 2951.23   620.6 2966.08   662.4 2972.56   695.9 2980.05
   716.8 2986.64   741.9 2996.37     779 3014.03   800.4 3027.43   804.7 3028.13
#Mann= 4 ,-1,0
       0      .1       0   394.7    .045       0   420.8      .1       0
  781.82     .06       0
Bank Sta=394.7,420.8
XS Rating Curve= 0 ,0
Exp/Cntr(USF)=0,0
Exp/Cntr=0.3,0.1

Type RM Length L Ch R = 1 ,14129   ,347.4,347.4,347.4
XS GIS Cut Line= 4
2270694.71600107517441.002047412 2270380.2954552517345.109449561
2270247.33605166517364.8456110242269923.39585612517228.716310718
#Sta/Elev= 30
       0 3111.05    65.4 3080.42   107.6 3053.28   162.1 3023.92   186.7 3012.34
     191 3009.09   199.2 3000.68   245.2 2973.75   274.9 2954.73   303.8 2934.01
   328.7 2911.26     345 2899.75   369.3 2885.98   373.3 2884.72   381.4 2884.56
   397.6  2885.8   409.7 2887.17   417.8 2885.98   425.9 2888.39   433.3 2892.81
   450.2 2906.52   463.1 2912.56   475.2 2916.18   492.6 2918.39   566.4 2918.34
   609.7 2922.83   635.8 2927.92   661.8 2937.54   740.2  2975.8   814.5 3007.11
#Mann= 3 ,-1,0
       0      .1       0   369.3    .045       0   397.6      .1       0
Bank Sta=369.3,397.6
XS Rating Curve= 0 ,0
Exp/Cntr(USF)=0,0
Exp/Cntr=0.3,0.1

Type RM Length L Ch R = 1 ,13782   ,282.5,282.5,282.5
XS GIS Cut Line= 4
2270690.04078215517199.9695428022270346.01685898517135.282890848
2270293.04084663 517026.214630132269919.73531741516984.030914968
#Sta/Elev= 30
       0 3085.17    54.8 3051.58    87.4 3036.06   119.9 3018.28   128.1 3009.29
   132.1 3006.46   168.8 2984.23     238  2937.7   282.7 2909.73   311.2 2897.23
   343.8 2889.17   365.7  2879.5   379.1 2875.17   392.4 2865.72     400 2863.32
   414.6 2862.72   423.5 2863.32   436.9 2867.22   476.2 2869.59   504.4 2877.16
   576.8 2882.59   592.4 2886.45   610.5 2894.12   657.3 2920.38   677.5 2927.37
   697.3 2936.36   721.8 2951.11   741.9 2966.51   786.2 2990.39     847 3020.78
#Mann= 4 ,-1,0
       0      .1       0     400    .045       0   423.5      .1       0
  841.31     .06       0
Bank Sta=400,423.5
XS Rating Curve= 0 ,0
Exp/Cntr(USF)=0,0
Exp/Cntr=0.3,0.1

Type RM Length L Ch R = 1 ,13499   ,372.1,372.1,372.1
XS GIS Cut Line= 4
2270770.35824746 517068.09687812 2270471.2576292516897.128804354
2270468.14139318516858.6952267672270084.16012413516660.150357862
#Sta/Elev= 30
       0 3090.46    11.7 3083.65    33.1 3068.39   110.7 3026.31   126.9 3008.59
   194.3 2965.52   231.6 2938.07   241.2 2928.11   251.3 2920.34   315.8 2878.35
   337.9  2862.4   348.5 2857.95     376  2854.2     392 2854.34     402 2850.63
   419.1 2849.59   429.9 2850.52   441.6 2856.78   447.3 2858.14   482.1 2856.44
   500.1 2857.51   532.6 2867.03   569.3 2882.53   612.7 2886.75   630.7 2890.92
   671.2 2908.27   755.2 2947.72   783.8 2965.31   792.8 2967.63   815.4 2977.85
#Mann= 3 ,-1,0
       0      .1       0     402    .045       0   429.9      .1       0
Bank Sta=402,429.9
XS Rating Curve= 0 ,0
Exp/Cntr(USF)=0,0
Exp/Cntr=0.3,0.1

Type RM Length L Ch R = 1 ,13127   ,314.5,314.5,314.5
XS GIS Cut Line= 5
2270892.72392133516894.9678178672270688.80282123516655.382543691
2270631.22441159516581.3502209432270526.75854817516578.515388519
2270267.70066236516304.715215706
#Sta/Elev= 30
       0 3056.48    27.2 3041.74    31.7  3036.2    38.5 3024.04    44.2 3019.79
    86.8 2994.27   170.4 2937.44   180.4 2928.68   194.6 2922.92   245.7 2888.41
   296.5 2849.64   309.4 2841.68   317.4 2838.84   367.8 2835.16     385 2831.89
   406.9 2832.96   439.5 2829.65   447.5 2828.47   456.6 2829.88   475.5 2847.65
   483.5 2850.51   539.9  2853.5   558.8 2850.28   589.3 2853.34   614.7 2864.58
   638.9 2870.75   665.6 2884.97   740.5  2937.7   813.5 2962.33   889.8  2978.4
#Mann= 3 ,-1,0
       0      .1       0   439.5    .045       0   456.6      .1       0
Bank Sta=439.5,456.6
XS Rating Curve= 0 ,0
Exp/Cntr(USF)=0,0
Exp/Cntr=0.3,0.1

Type RM Length L Ch R = 1 ,12813   ,276.8,276.8,276.8
XS GIS Cut Line= 2
2271092.65945431516723.294521453 2270618.1681381516258.581823749
#Sta/Elev= 30
       0  3022.4    51.1 2990.76    95.2 2961.87   106.5 2953.64   157.4 2923.88
   168.6 2915.77   179.8 2912.05   185.4 2908.09     219  2889.4   273.4 2864.32
   294.6 2851.39   323.2 2827.31   336.6 2822.84   344.1 2817.27   349.8 2815.16
   361.1 2814.25   383.7 2815.27   403.2 2818.93   420.5 2820.12   431.8 2822.97
   454.6 2823.21   488.9 2820.58   522.3 2824.18   544.9 2824.66   560.6 2829.46
   577.4 2838.32   605.4 2846.49   629.8  2855.1   654.7 2861.09   664.2 2862.49
#Mann= 3 ,-1,0
       0      .1       0   349.8    .045       0   383.7      .1       0
Bank Sta=349.8,383.7
XS Rating Curve= 0 ,0
Exp/Cntr(USF)=0,0
Exp/Cntr=0.3,0.1

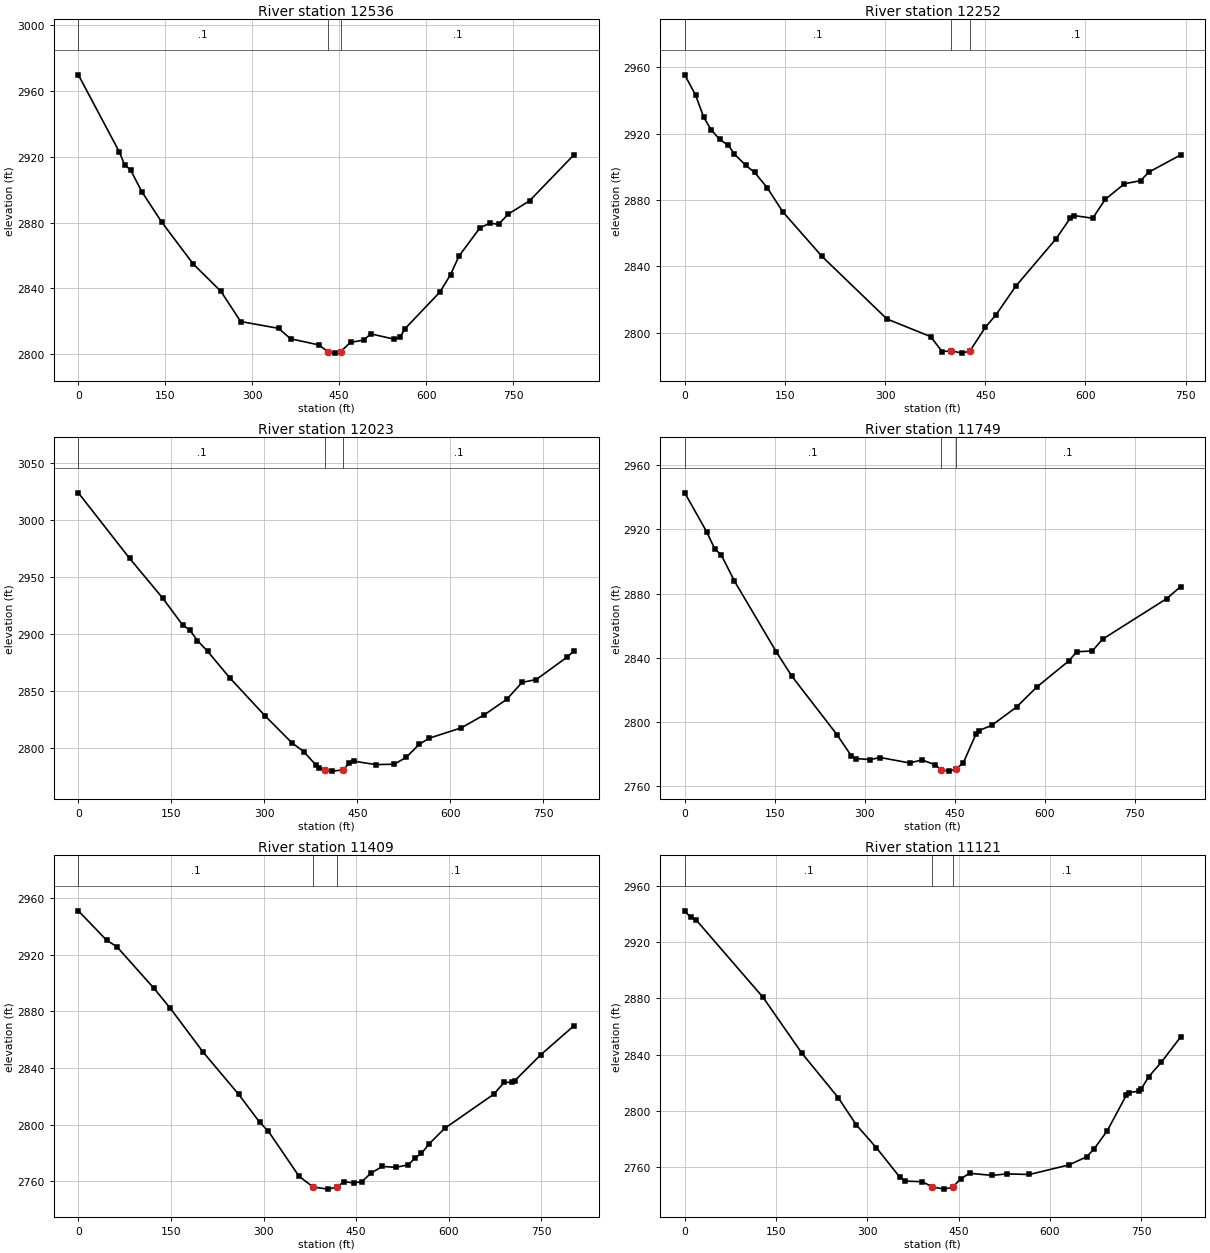
Type RM Length L Ch R = 1 ,12536   ,284.5,284.5,284.5
XS GIS Cut Line= 5
2271181.05150677516567.2471552982270975.69755611 516271.32183394
2270975.49653511516228.4582088842270840.45964089516200.412084699
2270661.74358835515941.684031619
#Sta/Elev= 30
       0 2969.85    70.7 2922.99    79.7 2915.23    90.2 2911.96   109.6 2898.74
   143.7 2880.36     198 2854.93     246 2838.19     280 2819.87   345.3 2815.73
   366.3 2809.37   414.6 2805.68430.91712801.468   442.5 2800.66452.61712801.628
   469.5 2807.21   492.2 2808.57   504.5 2812.37   544.9 2809.14   554.6 2810.22
   563.6 2815.53     624 2837.91   642.1 2848.44   656.7 2859.69     693 2876.92
   710.2 2879.66   724.8 2878.97   741.9 2885.25   778.3 2893.25   855.4  2921.4
#Mann= 3 ,-1,0
       0      .1       0430.9171    .045       0452.6171      .1       0
Bank Sta=430.9171,452.6171
XS Rating Curve= 0 ,0
Exp/Cntr(USF)=0,0
Exp/Cntr=0.3,0.1

Type RM Length L Ch R = 1 ,12252   ,228.5,228.5,228.5
XS GIS Cut Line= 3
2271394.70955414516441.1425246852271208.17549131516151.591053712
2271069.96755171515778.252337757
#Sta/Elev= 30
       0 2955.45    16.3  2943.2    28.5 2929.75    39.4 2922.47    52.3 2916.48
    65.5  2912.9    74.2 2907.76    91.5 2900.81   104.6 2896.67   123.4 2887.47
   146.5 2873.05   205.4 2846.05   302.8 2808.28   368.1 2797.68   385.4 2788.63
   399.2 2789.09   415.3 2787.71   427.2 2789.08   450.1 2803.28   466.4 2810.98
   495.7 2828.07     556 2856.63   577.3 2869.08   582.9 2870.63   610.9 2869.02
   629.6 2880.37   658.4 2889.79   682.5 2891.65     695 2896.83   742.5 2907.16
#Mann= 3 ,-1,0
       0      .1       0   399.2    .045       0   427.2      .1       0
Bank Sta=399.2,427.2
XS Rating Curve= 0 ,0
Exp/Cntr(USF)=0,0
Exp/Cntr=0.3,0.1

Type RM Length L Ch R = 1 ,12023   ,274.3,274.3,274.3
XS GIS Cut Line= 2
2271631.29294628516357.3171235322271178.63190932515697.697547098
#Sta/Elev= 30
       0 3023.85    82.6 2966.36     136 2931.44   168.1 2907.89   179.7 2903.34
   192.2 2894.08   208.8 2884.52     244 2861.53   300.9 2828.15   344.6 2804.25
     364  2796.4   383.4 2784.65   388.3 2782.33     398 2780.43   408.5 2779.41
   427.1 2780.42   436.8 2786.19   445.4 2788.08   479.9 2785.14   509.6 2785.48
     529 2791.48   549.8 2802.97   566.2 2808.36     618 2817.45   655.1 2828.95
   691.2 2842.49   715.8 2857.31   738.8 2859.88   787.8  2879.3     800 2885.15
#Mann= 3 ,-1,0
       0      .1       0     398    .045       0   427.1      .1       0
Bank Sta=398,427.1
XS Rating Curve= 0 ,0
Exp/Cntr(USF)=0,0
Exp/Cntr=0.3,0.1

Type RM Length L Ch R = 1 ,11749   ,340,340,340
XS GIS Cut Line= 4
2271667.86834829516163.0429005632271506.88673335515934.211874019
2271529.73913083515824.1048679622271371.09118214515420.127485691
#Sta/Elev= 30
       0 2942.81    36.5 2918.51    49.9 2907.93      61 2903.97    82.9  2887.7
   152.4 2843.69   178.3  2828.5   253.8 2791.88   277.5 2778.74   284.9    2777
   309.4 2776.43   325.8 2777.68   374.8 2774.28   395.4 2776.17   416.9 2773.19
   426.6 2770.16   440.3 2769.19   451.2 2770.22   464.1 2774.34   485.6 2792.62
   489.9 2794.48   511.4 2797.72   553.1 2809.25     587  2821.8   639.5 2837.81
   653.2 2843.66     679 2844.14   696.2 2851.51     803 2876.81   826.2 2884.32
#Mann= 3 ,-1,0
       0      .1       0   426.6    .045       0   451.2      .1       0
Bank Sta=426.6,451.2
XS Rating Curve= 0 ,0
Exp/Cntr(USF)=0,0
Exp/Cntr=0.3,0.1

Type RM Length L Ch R = 1 ,11409   ,287.5,287.5,287.5
XS GIS Cut Line= 4
2271981.80631345516071.9133643362271871.93376368515782.836457953
2271776.36919238515620.7921848882271684.86845232515329.062163472
#Sta/Elev= 30
       0 2951.03    45.7  2930.3    62.3 2925.71   122.7 2896.16   149.1 2882.07
   201.8 2851.34   259.7 2821.29   293.9 2801.46   307.3 2795.55   357.6 2763.32
   380.4 2755.84   404.1 2754.34     419 2755.83   430.1 2759.64   445.8 2758.71
   459.3 2759.62   473.7 2765.59   492.3 2770.39   513.7 2769.74   534.7  2771.5
   545.1 2776.37   555.7 2779.56   568.2 2786.34   593.4 2797.32     673 2821.48
   689.8  2829.9   702.4  2829.7   706.6 2830.87   748.5 2849.13   803.1 2869.97
#Mann= 3 ,-1,0
       0      .1       0   380.4    .045       0     419      .1       0
Bank Sta=380.4,419
XS Rating Curve= 0 ,0
Exp/Cntr(USF)=0,0
Exp/Cntr=0.3,0.1

Type RM Length L Ch R = 1 ,11121   ,348.1,348.1,348.1
XS GIS Cut Line= 4
2272197.86660259516058.3455694782272082.79906773515738.170408326
2272110.84519192515609.3659861462272040.45909111515273.984125161
#Sta/Elev= 30
       0 2942.44     9.7 2937.69    18.2  2936.2   128.8 2880.71   192.5 2841.03
     252 2809.44   281.8 2790.01   314.9 2773.66   353.5 2752.65   361.7 2749.96
   390.4 2749.48   406.7  2745.8   426.3 2744.21   440.7  2745.7   453.2 2751.51
   468.1  2755.5   504.9    2754   529.5 2755.07   566.2 2754.63   631.6  2761.5
   660.3 2767.22   672.5 2772.82     694 2785.66   725.6 2811.18   729.7 2812.93
   746.1 2813.97   750.2 2815.71   762.4 2824.35   782.9 2834.55   814.7 2852.55
#Mann= 3 ,-1,0
       0      .1       0   406.7    .045       0   440.7      .1       0
Bank Sta=406.7,440.7
XS Rating Curve= 0 ,0
Exp/Cntr(USF)=0,0
Exp/Cntr=0.3,0.1

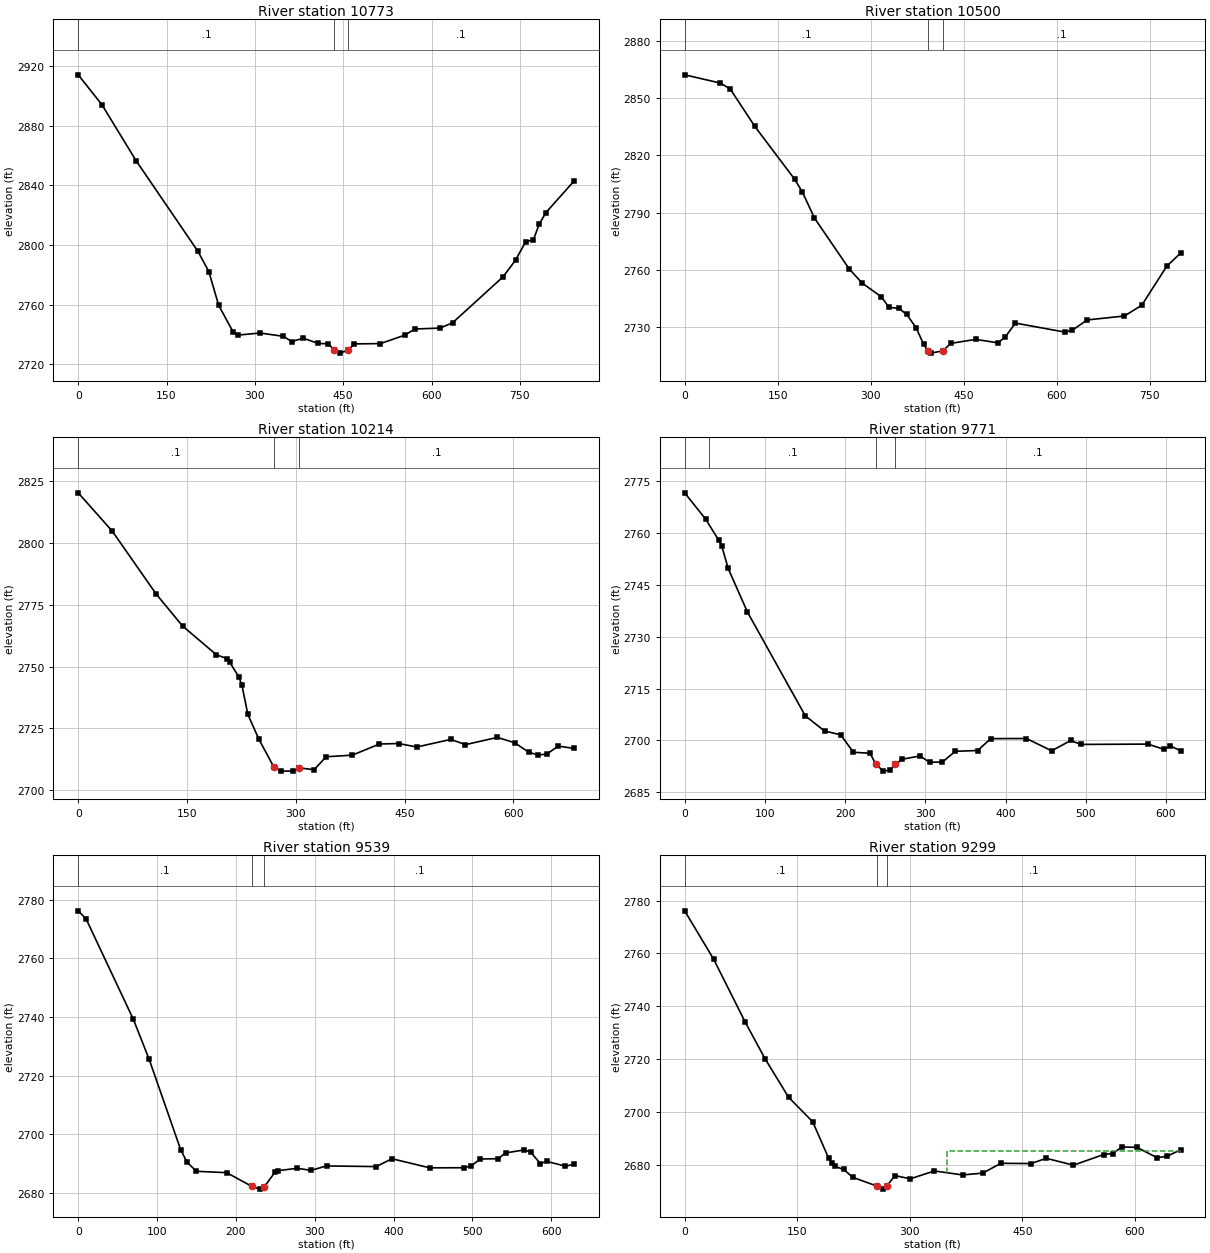
Type RM Length L Ch R = 1 ,10773   ,273,273,273
XS GIS Cut Line= 5
2272403.28429927515984.4776998832272334.90256179515711.266904016
2272414.15210317515599.3574733842272318.59425995515430.701787638
2272236.21548681 515216.53577653
#Sta/Elev= 30
       0 2914.07    40.5 2893.89    98.2 2856.56   203.2  2795.8   221.9  2782.1
   238.4 2759.63   263.2 2741.58   271.4 2739.61   308.7 2740.99   347.9  2738.8
   362.6  2735.3   382.2  2737.5   407.4 2734.02   424.8 2733.74434.81372729.486
   444.3 2727.51457.8137 2729.41   468.8 2733.69   513.2 2733.91   554.6 2739.56
   571.5 2743.67   614.2 2744.31   635.7 2747.86   721.4 2778.68   742.6 2789.86
     760  2802.3   772.8 2803.35   782.8 2813.99   794.2 2821.75   842.1 2842.95
#Mann= 3 ,-1,0
       0      .1       0434.8137    .045       0457.8137      .1       0
Bank Sta=434.8137,457.8137
XS Rating Curve= 0 ,0
Exp/Cntr(USF)=0,0
Exp/Cntr=0.3,0.1

Type RM Length L Ch R = 1 ,10500   ,286.4,286.4,286.4
XS GIS Cut Line= 2
2272648.14700414515982.5897062352272649.90612921515182.591640313
#Sta/Elev= 30
       0 2862.34    57.4 2858.03    73.4 2854.96   113.2 2835.23   177.4 2807.51
   189.8 2800.84   209.4 2787.11   265.4 2760.43     286 2753.08   317.4 2745.72
   329.4 2740.29   345.4 2739.67   358.2 2736.57   373.4 2729.47   385.4 2720.86
   392.6 2717.39   397.4 2716.21   416.5 2717.43   429.4 2721.33   469.4 2723.43
   505.4  2721.6   517.4 2724.77   533.4 2731.97   613.4 2727.25   625.4 2728.27
   649.4 2733.64   709.4 2735.71   737.4 2741.38   777.4 2761.74     800 2768.76
#Mann= 3 ,-1,0
       0      .1       0   392.6    .045       0   416.5      .1       0
Bank Sta=392.6,416.5
XS Rating Curve= 0 ,0
Exp/Cntr(USF)=0,0
Exp/Cntr=0.3,0.1

Type RM Length L Ch R = 1 ,10214   ,443.1,443.1,443.1
XS GIS Cut Line= 4
2272910.23168792515951.8705448022272887.82670636515770.371513871
2272930.41526531515615.5984581872272926.92852089515275.285124661
#Sta/Elev= 30
       0 2820.14      47 2804.65   107.5 2779.26   143.8 2766.38   190.6 2754.73
   204.9 2753.24     209 2751.65   221.5 2745.78   225.6 2742.55   233.9 2730.65
   249.2 2720.58269.96162709.261   279.5 2707.77   296.1  2707.8304.76162709.063
   325.2 2708.35   341.8 2713.57   377.8 2714.22   415.3 2718.72   441.8 2718.91
   466.8 2717.51   513.8 2720.59   533.8 2718.46   577.8 2721.38   601.8 2719.22
   621.2 2715.38   633.8  2714.3   645.8 2714.62   661.8 2717.87   683.7 2716.94
#Mann= 3 ,-1,0
       0      .1       0269.9616    .045       0304.7616      .1       0
Bank Sta=269.9616,304.7616
XS Rating Curve= 0 ,0
Exp/Cntr(USF)=0,0
Exp/Cntr=0.3,0.1

Type RM Length L Ch R = 1 ,9771    ,231.4,231.4,231.4
XS GIS Cut Line= 4
2273337.15602272515883.3133523512273326.76856932515667.254321596
2273346.50473079515601.8133651662273358.44134274515268.501733502
#Sta/Elev= 30
       0 2771.58    26.2 2763.95    42.2 2757.97    46.2 2756.22    54.2 2749.73
    78.2 2737.13   150.3 2707.14   174.3 2702.74   194.4 2701.64   210.4 2696.59
     231 2696.31   238.4  2693.1   247.7 2691.14   256.1 2691.43   262.7 2693.09
   271.1 2694.58   293.3 2695.52   305.3  2693.7   321.3 2693.77   337.3 2696.87
   365.3  2697.1   381.4 2700.53     426 2700.57   457.4 2697.02   481.4 2700.01
   493.4 2698.86   577.5 2698.95   597.5 2697.43   605.5 2698.38   618.2 2697.06
#Mann= 4 ,-1,0
       0     .08       0      30      .1       0   238.4    .045       0
   262.7      .1       0
Bank Sta=238.4,262.7
XS Rating Curve= 0 ,0
Exp/Cntr(USF)=0,0
Exp/Cntr=0.3,0.1

Type RM Length L Ch R = 1 ,9539    ,239.7,239.7,239.7
XS GIS Cut Line= 2
2273548.02132678515907.2044951752273554.48567785515278.119920097
#Sta/Elev= 30
       0 2776.21      10 2773.44      70 2739.18      90 2725.56     130 2694.74
     138  2690.5     150 2687.38   188.3 2686.91   219.9  2682.3     230  2681.3
   236.3 2682.18     250 2687.22     254 2687.61     278 2688.42   295.2 2687.69
     315 2689.21     378 2688.99     398 2691.66     446 2688.56   489.2  2688.6
   498.1 2689.16   510.1 2691.57   532.7 2691.67   542.1 2693.65   566.1 2694.68
   574.1 2693.88   586.1 2690.02   594.1 2690.77   618.1 2689.12   629.1  2689.8
#Mann= 3 ,-1,0
       0      .1       0   219.9    .045       0   236.3      .1       0
Bank Sta=219.9,236.3
XS Rating Curve= 0 ,0
Exp/Cntr(USF)=0,0
Exp/Cntr=0.3,0.1

Type RM Length L Ch R = 1 ,9299    ,298.7,305.3,308.6
XS GIS Cut Line= 3
2273747.84516771 515919.62321532 2273791.5351523515744.402880367
2273735.28700188515267.301815627
#Sta/Elev= 30
       0 2776.11    38.6 2757.84    80.8 2734.02   107.2  2720.2   138.6 2705.65
   170.6 2696.44   191.9 2682.67   195.9 2680.78   199.9  2679.6     212 2678.41
   224.1 2675.44   256.3 2672.14   264.4 2670.99   269.4 2672.22   280.5  2676.1
   300.6 2674.88   332.9 2677.86   370.3 2676.35   397.3 2677.05   421.5 2680.75
   461.7 2680.65     482 2682.62   518.1 2680.04   558.4 2684.06   570.5 2684.44
   582.8 2686.91   602.7 2686.78   629.7 2682.86     643  2683.4     661 2685.85
#Mann= 3 ,-1,0
       0      .1       0   256.3    .045       0   269.4      .1       0
#XS Ineff= 2 , 0
                          349.41         2685.55
Permanent Ineff=
       F       F
Bank Sta=256.3,269.4
XS Rating Curve= 0 ,0
Exp/Cntr(USF)=0,0
Exp/Cntr=0.3,0.1