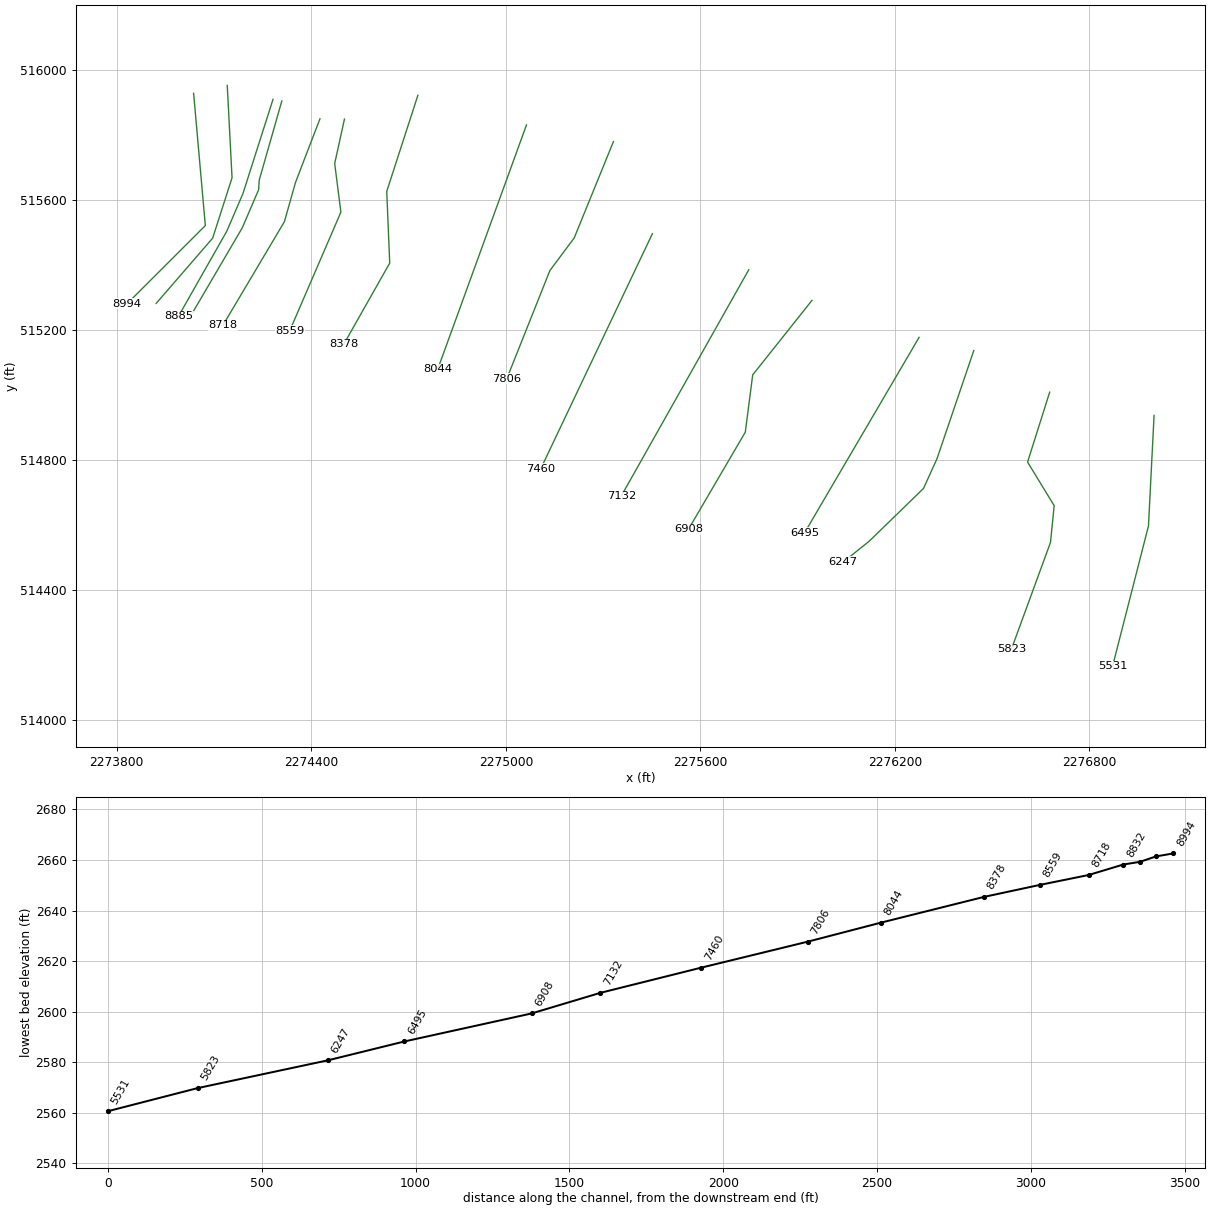
HEC-RAS study LTHRBRKRN.prj: LTHRBRKRN

--- LTHRBRKRN.g01 (geometry) --- (continued)

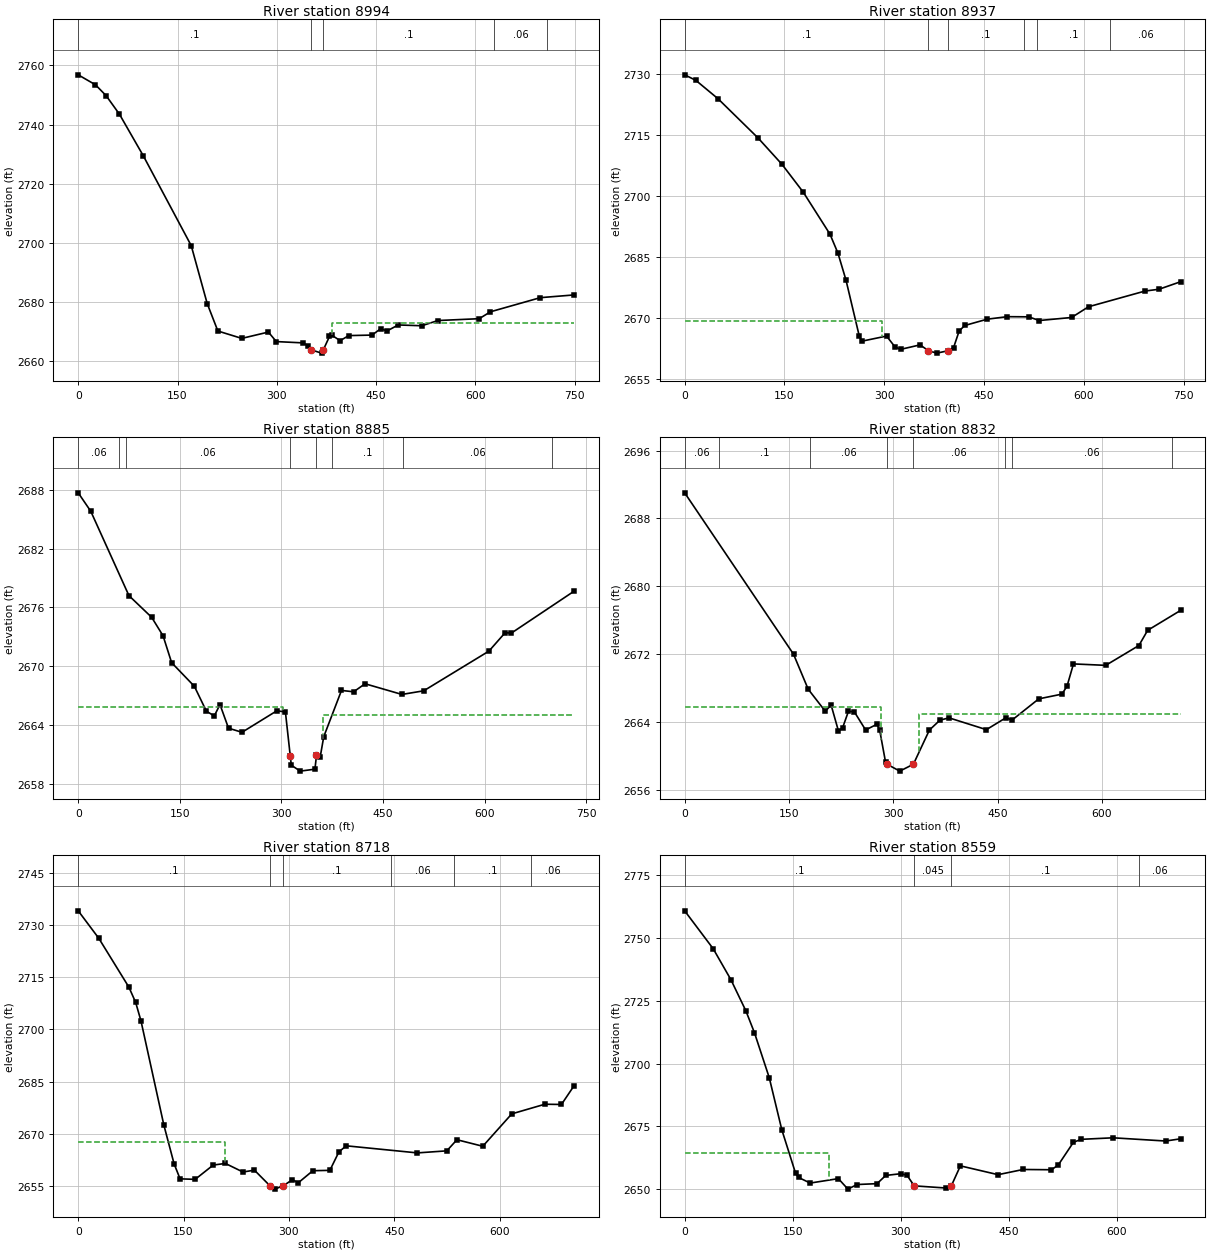
Type RM Length L Ch R = 1 ,8994    ,66.1,56.7,49.9
XS GIS Cut Line= 3
2274036.91330459515927.2208403142274073.09288822515520.200524431
  2273831.895664515280.008288638
#Sta/Elev= 30
       0 2756.84    26.1 2753.46    42.2 2749.77    62.3 2743.49    98.4 2729.38
   170.7 2698.99   194.8 2679.39   210.9 2670.09     247 2667.59   287.2 2669.73
   299.2 2666.51   339.4 2666.07   346.9 2665.14   351.6 2663.73   367.5  2662.6
     370 2663.63   379.5 2668.26   383.5  2668.6   395.6 2666.82   408.6 2668.54
   443.8 2668.71   456.7 2670.86   466.4 2670.11   483.3 2672.14   518.9 2671.87
   543.3 2673.64   605.6 2674.26   622.6  2676.6   697.8 2681.38     749 2682.31
#Mann= 5 ,-1,0
       0      .1       0   351.6    .045       0     370      .1       0
  628.63     .06       0  708.63      .1       0
#XS Ineff= 2 , 0
                          383.41         2672.73
Permanent Ineff=
       F       F
Bank Sta=351.6,370
XS Rating Curve= 0 ,0
Exp/Cntr(USF)=0,0
Exp/Cntr=0.3,0.1

Type RM Length L Ch R = 1 ,8937    ,52,52,52
BEGIN DESCRIPTION:
structure xs 4
END DESCRIPTION:
XS GIS Cut Line= 4
 2274140.6908164 515951.241199572274155.46408346515667.317473258
2274095.67851832515481.4974735172273921.40013348515280.673374419
#Sta/Elev= 30
       0 2729.88    16.7 2728.53    50.1    2724   110.2 2714.36   146.3 2707.85
   178.3 2700.99   218.4 2690.67   230.4 2685.99   242.4 2679.41   262.4 2665.62
   266.4 2664.35   303.4 2665.61     316 2662.96   324.4 2662.33   353.8 2663.44
   366.4    2662     379 2661.41   395.8 2661.99   404.2 2662.79   412.6 2666.88
     421 2668.21   454.6 2669.76   484.9 2670.38     517 2670.34   532.9 2669.43
   581.5 2670.18     607 2672.82   691.8 2676.68     713 2677.13   745.4 2678.98
#Mann= 6 ,-1,0
       0      .1       0   366.4    .045       0   395.8      .1       0
  509.51     .06       0  529.51      .1       0  639.51     .06       0
#XS Ineff= 2 , 0
          296.11  2669.4
Permanent Ineff=
       F       F
Bank Sta=366.4,395.8
XS Rating Curve= 0 ,0
Exp/Cntr(USF)=0,0
Exp/Cntr=0.5,0.3

Type RM Length L Ch R = 1 ,8885    ,53.9,53.9,53.9
BEGIN DESCRIPTION:
structure xs 3; 10.1 ft between structure and xs
END DESCRIPTION:
XS GIS Cut Line= 4
2274281.82295286515908.5246441132274189.05052904515618.461240344
2274139.51484126515503.4139614492273989.93551228515240.611390387
#Sta/Elev= 30
       0 2687.72    18.5 2685.84    74.9 2677.21   108.5 2674.99   125.3  2673.1
   137.9 2670.36   171.5 2667.94   189.2  2665.4   200.9 2664.91   209.3 2666.08
   221.9 2663.66   241.8 2663.24   293.3 2665.44   305.9 2665.32     313 2660.86
   314.6 2659.88   327.7 2659.27   349.5 2659.47   351.8 2660.88   357.3 2660.73
   362.5 2662.79   388.7 2667.52   406.6 2667.38   423.5  2668.2   477.9 2667.11
   510.1 2667.48   606.4 2671.54   630.3 2673.42   639.5 2673.38   732.2 2677.67
#Mann= 8 ,-1,0
       0     .06       0      60      .1       0      70     .06       0
     313    .045       0   351.8     .06       0  374.54      .1       0
   479.8     .06       0   699.8      .1       0
#XS Ineff= 2 , 0
             303  2665.8     362            2665
Permanent Ineff=
       F       F
Bank Sta=313,351.8
XS Rating Curve= 0 ,0
Exp/Cntr(USF)=0,0
Exp/Cntr=0.5,0.3

Type RM Length L Ch R = 1 ,8832    ,113,113,113
BEGIN DESCRIPTION:
structure xs 2; 25.7 ft between structure and xs
END DESCRIPTION:
XS GIS Cut Line= 5
2274309.04846823515903.6165723812274239.29775738515659.959116684
2274237.51423163515630.5771659922274187.18598116515513.650796776
2274033.82042541515252.362716421
#Sta/Elev= 30
       0 2691.02   156.5    2672   177.6 2667.87   202.2 2665.27   210.6    2666
   221.2 2662.92   227.2 2663.34   235.5 2665.26   243.9 2665.21   260.2 2663.06
   276.3 2663.73   280.3  2663.1   288.8  2659.3   291.1 2659.02   309.3 2658.21
   328.9 2659.02   351.9 2663.05   367.1 2664.22   380.2 2664.49   433.9  2663.1
   461.7 2664.49     471 2664.24   509.2 2666.73   542.6 2667.29   549.9 2668.24
   559.1 2670.85   605.5 2670.68   653.2 2673.02   665.8 2674.81   713.2 2677.16
#Mann= 8 ,-1,0
       0     .06       0      50      .1       0     180     .06       0
   291.1    .045       0   328.9     .06       0  460.18      .1       0
  470.18     .06       0  700.18      .1       0
#XS Ineff= 2 , 0
             283  2665.8     337            2665
Permanent Ineff=
       F       F
Bank Sta=291.1,328.9
XS Rating Curve= 0 ,0
Exp/Cntr(USF)=0,0
Exp/Cntr=0.5,0.3

Type RM Length L Ch R = 1 ,8718    ,160.2,159.6,156.9
BEGIN DESCRIPTION:
structure xs 1
END DESCRIPTION:
XS GIS Cut Line= 5
2274426.64379211515848.4788750112274398.01052957515774.525879291
2274351.26698927515652.9926744912274316.98898386515532.292120651
2274127.26927687515213.384627149
#Sta/Elev= 30
       0 2734.11    29.3 2726.21    72.2 2712.14    81.8 2707.76    89.3  2702.5
     122 2672.43   136.5 2661.35     145 2657.02   166.5 2656.87   192.2 2660.98
   209.5 2661.45   234.5 2658.99   250.9 2659.51   273.4 2654.94     280 2654.06
292.03922655.039     305 2656.77   313.3 2655.88   334.1 2659.36   358.3 2659.46
   371.2 2664.78   381.6 2666.52   482.9 2664.48   524.8 2665.07   539.2 2668.27
     576 2666.39   617.3 2675.71   664.4 2678.48     688 2678.41   706.1 2683.84
#Mann= 6 ,-1,0
       0      .1       0   273.4    .045       0292.0392      .1       0
  444.99     .06       0  534.99      .1       0  644.99     .06       0
#XS Ineff= 2 , 0
          209.13 2667.51
Permanent Ineff=
       F       F
Bank Sta=273.4,292.0392
XS Rating Curve= 0 ,0
Exp/Cntr(USF)=0,0
Exp/Cntr=0.3,0.1

Type RM Length L Ch R = 1 ,8559    ,174.4,180.9,187.9
XS GIS Cut Line= 4
2274502.22294966515847.8267540062274472.07329663515711.148326944
2274491.16807688515561.405050236 2274333.3848927515196.594248593
#Sta/Elev= 30
       0 2760.66    39.6 2745.59    64.2 2733.29    84.9 2720.96    96.9  2712.2
   117.4 2694.37   134.8 2673.71     154 2656.34   158.1 2654.74   174.2 2652.52
   213.3 2654.28   226.6 2650.11   239.2 2651.94     267 2652.28   279.1 2655.55
   299.9 2656.23   308.6 2655.63   318.6 2651.41   363.3 2650.54   370.1  2651.4
   382.7 2659.35     435 2655.85   469.8 2657.91   509.1 2657.81   518.5 2659.67
   539.6 2668.71   550.4 2669.89   594.6  2670.5   667.6 2669.22   688.4  2670.1
#Mann= 4 ,-1,0
       0      .1       0   318.6    .045       0   370.1      .1       0
  630.92     .06       0
#XS Ineff= 2 , 0
          200.73  2664.3
Permanent Ineff=
       F       F
Bank Sta=318.6,370.1
XS Rating Curve= 0 ,0
Exp/Cntr(USF)=0,0
Exp/Cntr=0.3,0.1

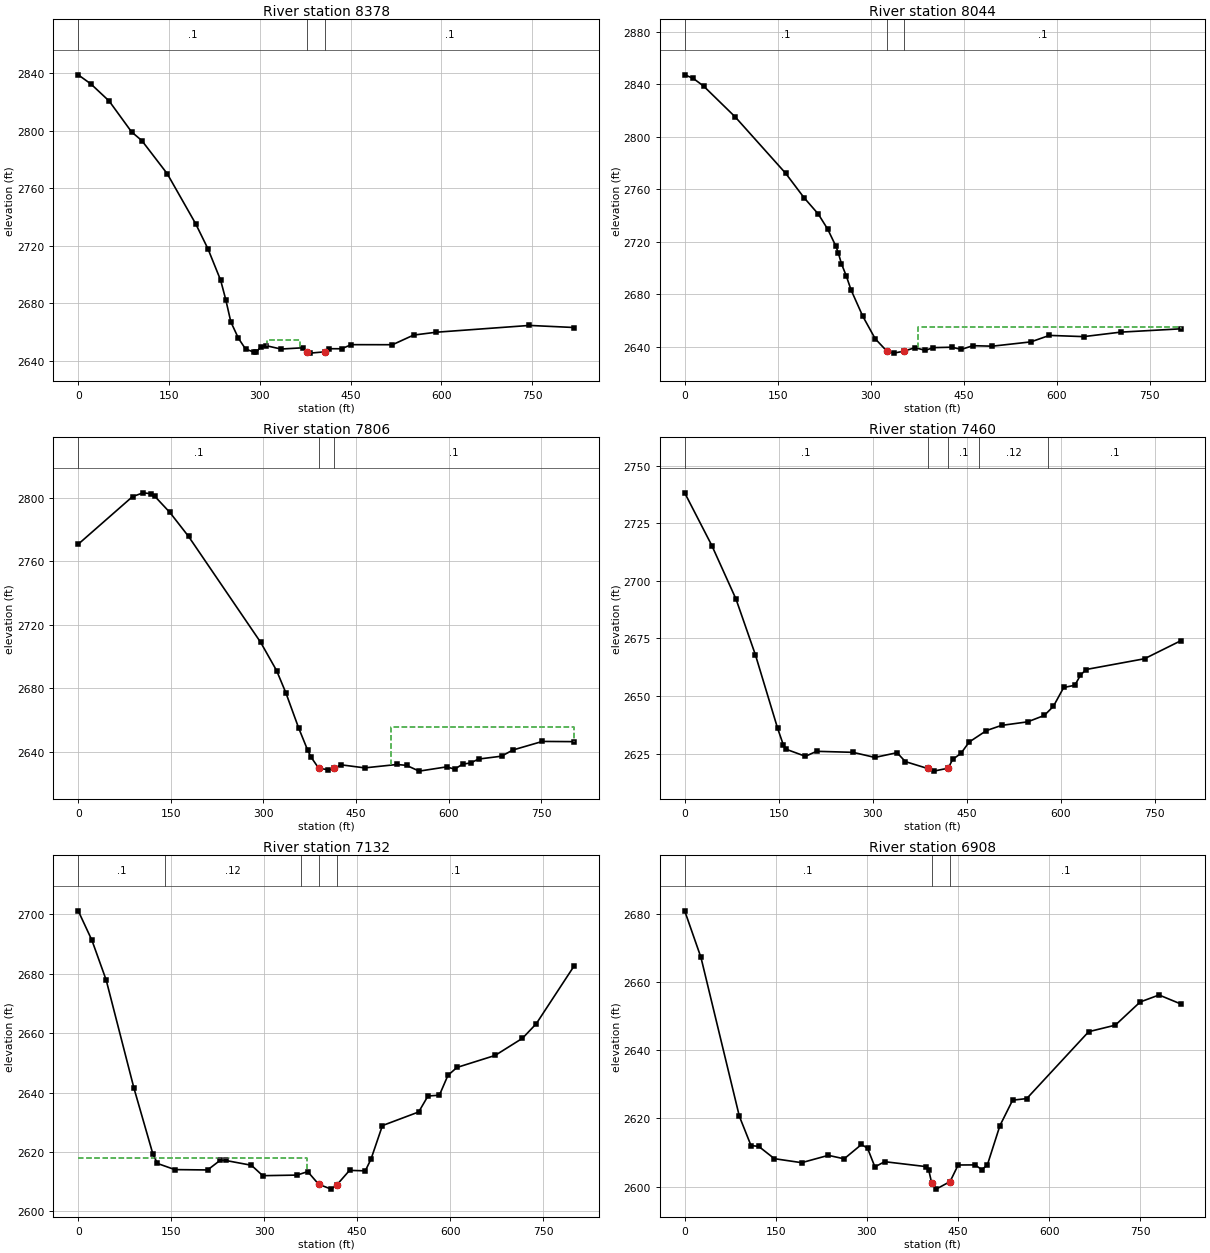
Type RM Length L Ch R = 1 ,8378    ,334.3,334.3,334.3
XS GIS Cut Line= 4
2274728.75795623515921.0435410152274632.59444304515625.259828596
2274641.82773496515404.8149841832274499.73461463515154.526542505
#Sta/Elev= 30
       0 2838.67    20.9 2832.35    51.1 2820.48    88.2 2799.01   105.1    2793
   147.1 2769.99     194  2735.3   214.4 2717.82   235.4 2695.93   243.8 2682.55
   252.2 2667.06   264.8 2655.64   276.5 2648.25   290.1  2646.1   294.3  2646.4
   302.7 2649.89   310.5 2650.55   335.1 2648.22   371.2 2649.09   378.4 2646.09
   383.2 2645.38   407.7 2646.29   415.2 2648.44   435.2 2648.41   451.2 2651.26
   519.3 2651.22   554.2 2657.92   591.7  2659.9   745.7 2664.62   819.5 2663.17
#Mann= 3 ,-1,0
       0      .1       0   378.4    .045       0   407.7      .1       0
#XS Ineff= 1 ,-1
  311.58  366.67 2654.21
Permanent Ineff=
       F
Bank Sta=378.4,407.7
XS Rating Curve= 0 ,0
Exp/Cntr(USF)=0,0
Exp/Cntr=0.3,0.1

Type RM Length L Ch R = 1 ,8044    ,237.6,237.6,237.6
XS GIS Cut Line= 2
2275063.68097586515829.8946681962274789.82836911 515078.22668978
#Sta/Elev= 30
       0 2847.16    13.5 2844.56    30.6 2838.55    81.3  2815.2   162.8 2772.21
   192.3 2753.73   215.5 2741.14   230.7 2729.63   243.6 2716.97   247.7 2711.73
   252.9 2703.27   260.5 2694.24   268.5 2683.21   287.2  2663.4   307.3 2646.18
   325.7 2636.96   337.2 2635.22   354.1 2636.74   371.5 2639.39   388.2 2637.32
   400.9  2639.4   430.9 2639.72   446.4 2638.05   464.8 2640.89   496.3 2640.51
   558.5 2643.79   588.3 2648.72   643.6 2647.79   703.2  2651.2     800 2653.72
#Mann= 3 ,-1,0
       0      .1       0   325.7    .045       0   354.1      .1       0
#XS Ineff= 2 , 0
       0                     376       0 2654.88
Permanent Ineff=
       F       F
Bank Sta=325.7,354.1
XS Rating Curve= 0 ,0
Exp/Cntr(USF)=0,0
Exp/Cntr=0.3,0.1

Type RM Length L Ch R = 1 ,7806    ,346.2,346.2,346.2
XS GIS Cut Line= 4
2275331.87844254515778.6199821592275210.82934907515482.143803951
2275135.80885228515381.7317544012275002.99627998515049.348754734
#Sta/Elev= 30
       0 2770.64      88 2800.63   105.2 2803.01   117.5 2802.46   123.6 2801.02
   148.5 2790.66   178.7 2775.58   295.4 2708.95   321.4 2691.05   336.4 2677.05
   357.1 2654.92   371.5 2641.14   377.1 2636.58  389.69 2629.51   404.9 2628.58
   414.3 2629.44   425.7 2631.68   464.2 2629.75   516.5 2631.88   531.9 2631.33
   552.4  2627.7   596.9 2630.38   609.9 2628.94   622.8  2632.1   635.7 2632.83
   648.6  2635.3   685.8 2637.11   704.2    2641     752 2646.41   803.5 2646.27
#Mann= 3 ,-1,0
       0      .1       0  389.69    .045       0   414.3      .1       0
#XS Ineff= 2 , 0
       0                  506.64       0 2655.67
Permanent Ineff=
       F       F
Bank Sta=389.69,414.3
XS Rating Curve= 0 ,0
Exp/Cntr(USF)=0,0
Exp/Cntr=0.3,0.1

Type RM Length L Ch R = 1 ,7460    ,328.2,328.2,328.2
XS GIS Cut Line= 2
2275451.96217812515495.1001108842275107.99198746 514772.82280407
#Sta/Elev= 30
       0 2738.22    43.3 2715.35    81.9 2692.08   112.9 2667.85   148.3 2635.97
   157.2 2628.96   161.6 2626.94   192.6 2623.85   210.4 2626.02   268.4 2625.58
   303.4 2623.37   338.8 2625.42   352.1 2621.55   387.6 2618.57   397.4 2617.42
  420.48 2618.71   427.4 2622.47   440.7 2625.13     454 2630.07   481.5 2635.03
   505.5 2637.27   547.1 2638.81   573.7 2641.59   588.2 2645.53   604.7 2653.74
   622.4 2654.68   631.2 2658.94   640.1 2661.52   733.6  2666.2   791.2 2673.98
#Mann= 5 ,-1,0
       0      .1       0   387.6    .045       0  420.48      .1       0
     470     .12       0     580      .1       0
Bank Sta=387.6,420.48
XS Rating Curve= 0 ,0
Exp/Cntr(USF)=0,0
Exp/Cntr=0.3,0.1

Type RM Length L Ch R = 1 ,7132    ,223.2,223.2,223.2
XS GIS Cut Line= 2
2275749.30172702515384.4085771232275355.76542446514687.896424629
#Sta/Elev= 30
       0 2701.22    22.1  2691.3    45.1  2677.9      90 2641.39   120.6 2619.17
   127.8 2616.09   155.9 2614.02   208.7  2613.9   228.8 2617.12   237.9  2617.1
   279.4 2615.48   297.7 2611.97   352.9 2612.17   370.2 2613.34   387.92609.069
     408 2607.44   417.5 2608.94   437.7 2613.76   463.1  2613.6   472.3 2617.55
   490.7 2628.85   549.2 2633.44   564.2 2638.82   582.6 2639.09   596.4 2645.78
   610.9 2648.44   672.5 2652.49   716.6 2658.27   738.8 2663.15     800 2682.66
#Mann= 5 ,-1,0
       0      .1       0     140     .12       0     360      .1       0
   387.9    .045       0   417.5      .1       0
#XS Ineff= 2 , 0
          369.58 2617.95
Permanent Ineff=
       F       F
Bank Sta=387.9,417.5
XS Rating Curve= 0 ,0
Exp/Cntr(USF)=0,0
Exp/Cntr=0.3,0.1

Type RM Length L Ch R = 1 ,6908    ,413.3,413.3,413.3
XS GIS Cut Line= 4
2275944.28998272515290.1605519662275761.36437936515060.874860439
2275738.51198187514884.6344010582275563.60502705514586.542072588
#Sta/Elev= 30
       0 2680.85    26.8 2667.19      90 2620.66   109.2 2612.07     122 2611.81
   147.7 2608.22   192.6 2607.05   236.6  2609.2   262.6 2608.18   291.1 2612.38
   301.1 2611.29   313.2 2605.82   329.3 2607.34   397.9 2605.89   401.9 2604.86
406.52982601.226     414  2599.3436.95722601.506   450.3 2606.37   478.2  2606.4
     489 2605.03   498.2 2606.29   519.1 2617.92     540 2625.37   563.2 2625.83
   665.2 2645.43   709.1 2647.35     750 2654.14   781.1 2656.19   816.6 2653.58
#Mann= 3 ,-1,0
       0      .1       0406.5298    .045       0436.9572      .1       0
Bank Sta=406.5298,436.9572
XS Rating Curve= 0 ,0
Exp/Cntr(USF)=0,0
Exp/Cntr=0.3,0.1

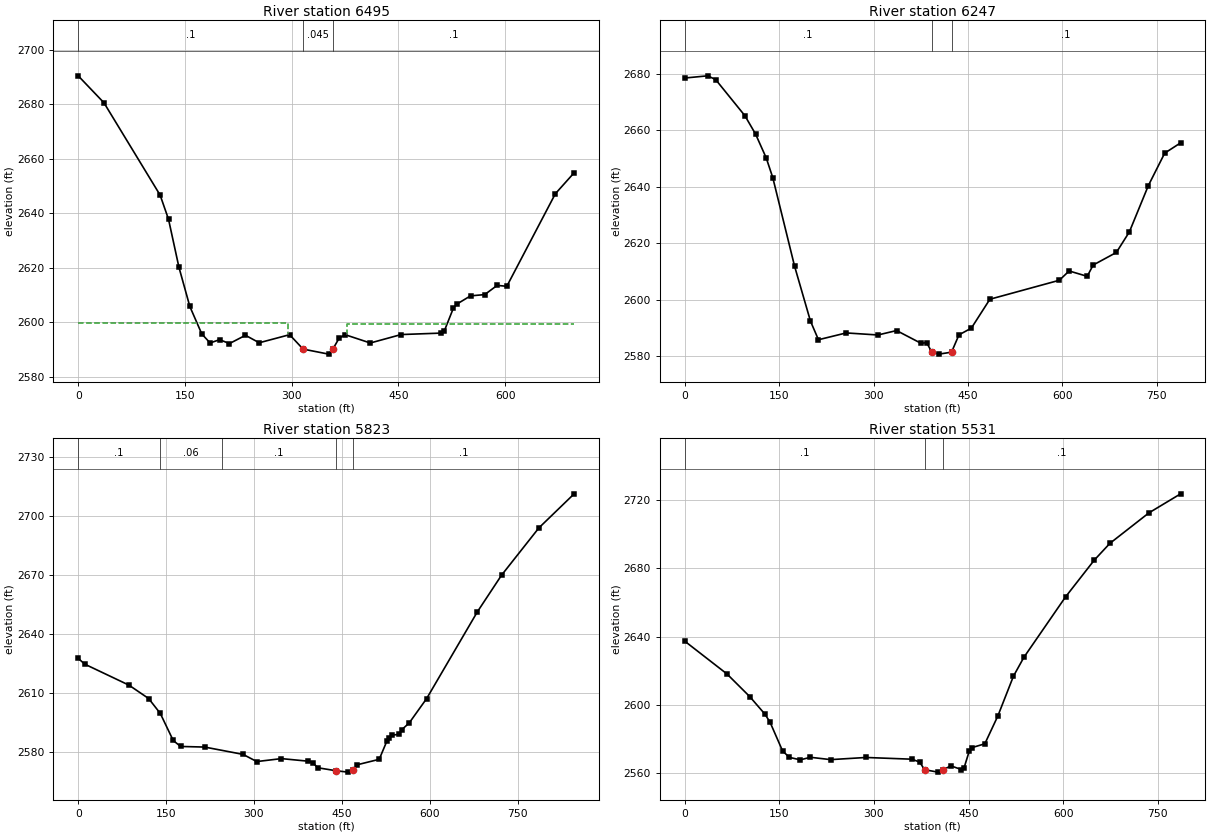
Type RM Length L Ch R = 1 ,6495    ,247.9,247.9,247.9
XS GIS Cut Line= 2
2276274.64935738515176.3913319272275921.65607455514575.637247282
#Sta/Elev= 30
       0 2690.43    36.2 2680.52   115.1 2646.61   126.9 2637.73   141.5 2620.15
   156.8 2605.74   173.6 2595.65   185.3 2592.32   198.6 2593.53   212.5  2592.1
     235 2595.14   254.3 2592.39     297 2595.36315.97572590.063   351.9 2588.22
  357.65 2590.01   366.5 2594.04   374.9 2595.37   410.4 2592.31   453.7 2595.41
   509.4 2595.94   514.1 2596.55   527.2 2605.17   532.6 2606.69   551.2 2609.62
   571.1 2610.08   588.6 2613.46   602.2 2613.14   670.4 2647.13   696.8 2654.84
#Mann= 3 ,-1,0
       0      .1       0315.9757    .045       0  357.65      .1       0
#XS Ineff= 2 , 0
           294.2 2599.78  377.41         2599.39
Permanent Ineff=
       F       F
Bank Sta=315.9757,357.65
XS Rating Curve= 0 ,0
Exp/Cntr(USF)=0,0
Exp/Cntr=0.3,0.1

Type RM Length L Ch R = 1 ,6247    ,424.1,424.1,424.1
XS GIS Cut Line= 5
2276443.29203411515135.7356246352276329.78134775514803.018198578
2276288.23153414514711.6086086432276120.99353437514549.564335577
2276040.59720098514485.210186522
#Sta/Elev= 30
       0 2678.58    36.5 2679.36    49.2 2678.03    95.7 2665.22   112.6 2658.73
   129.5  2650.3     140 2643.26   174.6  2611.9   199.8 2592.48   212.5 2585.88
   256.6 2588.29     307 2587.56   336.6 2589.13   375.3 2584.63   384.4 2584.84
   392.3 2581.59   403.8 2580.78   423.9 2581.47   435.7 2587.61   455.4 2589.99
   484.8 2600.22   595.2 2606.95   610.7 2610.24   639.4 2608.34   648.9 2612.34
   685.7 2616.79   706.4 2624.08   736.6 2640.51   762.5 2651.97   787.8 2655.62
#Mann= 3 ,-1,0
       0      .1       0   392.3    .045       0   423.9      .1       0
Bank Sta=392.3,423.9
XS Rating Curve= 0 ,0
Exp/Cntr(USF)=0,0
Exp/Cntr=0.3,0.1

Type RM Length L Ch R = 1 ,5823    ,291.7,291.7,291.7
XS GIS Cut Line= 5
 2276677.4332974515007.8038091672276609.20384425514792.630745176
2276691.26472612514658.6325962952276679.83852738514545.409354217
2276559.22678855514216.803342124
#Sta/Elev= 30
       0  2627.7    11.1 2624.75    86.7 2614.05   120.2 2607.25   140.1 2599.67
   162.2 2585.88   174.8 2582.84   215.9 2582.53   281.4 2578.81   304.8 2575.15
     347 2576.65   392.4 2575.34   400.4  2574.6   408.9    2572   440.6 2570.46
   460.7 2569.77   468.7  2570.6   476.8 2573.55   513.9 2576.29   526.7 2585.38
     531 2587.33   535.3 2588.55     548 2589.05   552.3 2591.34   565.1 2594.81
   594.9 2607.24   681.4 2651.36   722.7 2670.02   786.6 2694.15   846.7 2711.46
#Mann= 5 ,-1,0
       0      .1       0     140     .06       0  245.73      .1       0
   440.6    .045       0   468.7      .1       0
Bank Sta=440.6,468.7
XS Rating Curve= 0 ,0
Exp/Cntr(USF)=0,0
Exp/Cntr=0.3,0.1

Type RM Length L Ch R = 1 ,5531    ,263.8,263.8,263.8
XS GIS Cut Line= 3
 2276999.3636398514936.1782869082276982.11342137514596.307875885
2276871.33730486 514164.59991317
#Sta/Elev= 30
       0 2637.43    67.1 2618.16   103.1 2604.91   127.2 2594.61   135.2 2589.97
   155.2 2573.01     166 2569.28   183.2 2567.83   199.3 2569.33   231.3 2567.96
   287.4 2569.22   360.1 2568.21   372.4 2566.51   380.3 2562.03   401.4 2560.63
   409.6 2562.07     422 2564.29   438.5 2562.16   442.6 2562.92   450.9  2572.8
     455 2574.96   475.7 2577.24   496.3 2593.52   521.1 2616.91   537.6 2627.93
   603.7 2663.39   649.1 2684.89   673.9 2694.73   735.8 2712.62     786 2723.77
#Mann= 3 ,-1,0
       0      .1       0   380.3    .045       0   409.6      .1       0
Bank Sta=380.3,409.6
XS Rating Curve= 0 ,0
Exp/Cntr(USF)=0,0
Exp/Cntr=0.3,0.1