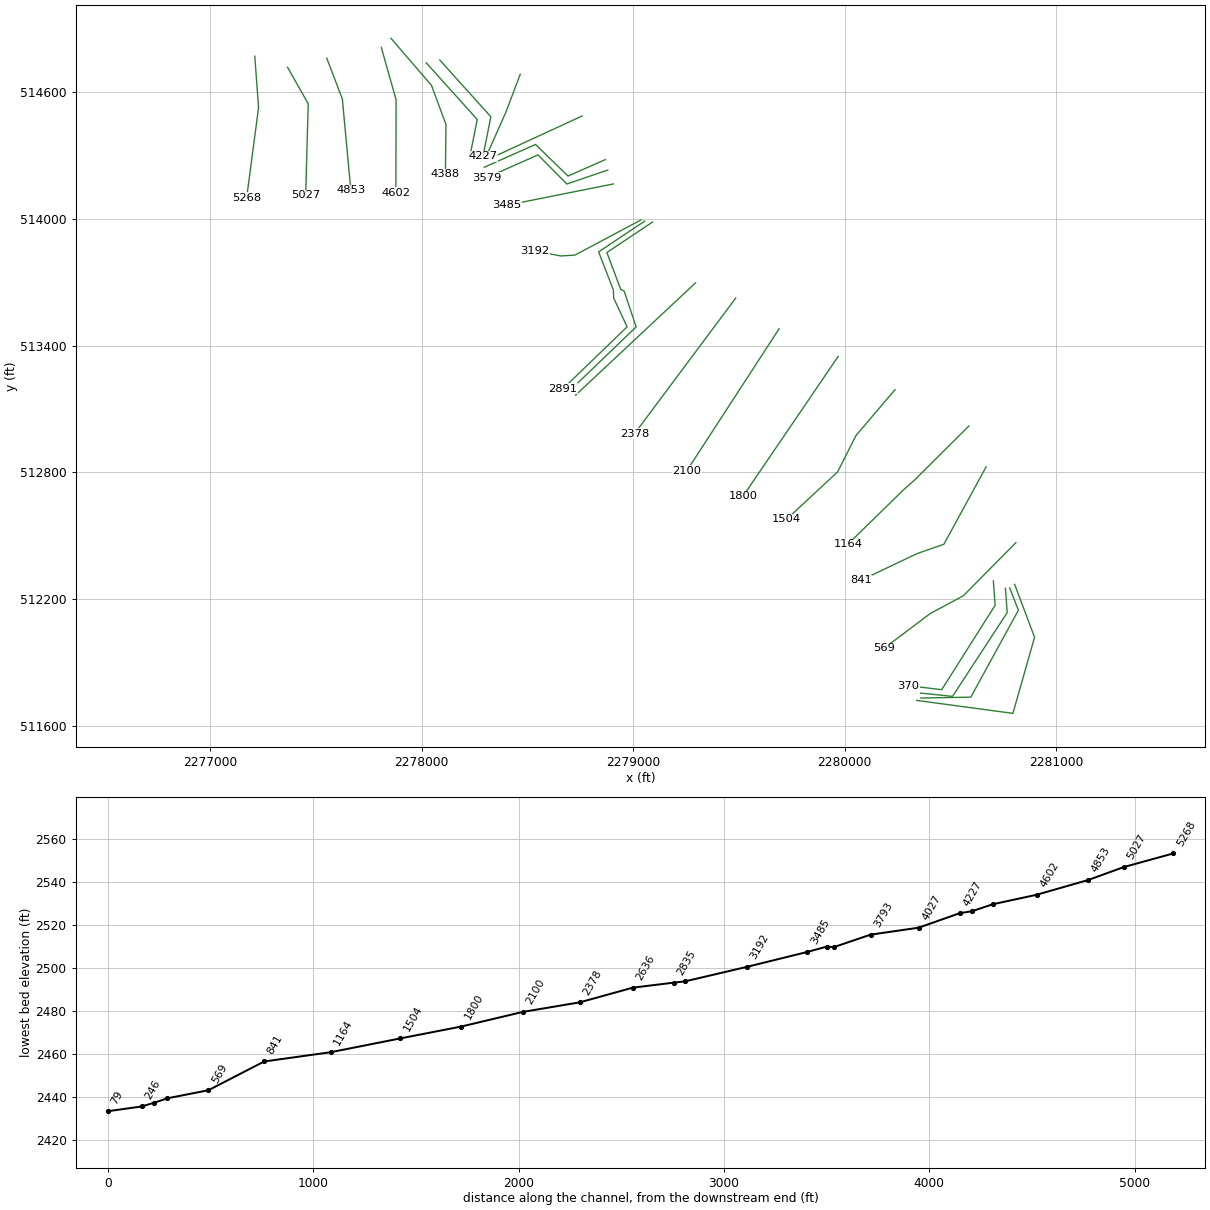
HEC-RAS study LTHRBRKRN.prj: LTHRBRKRN

--- LTHRBRKRN.g01 (geometry) --- (continued)

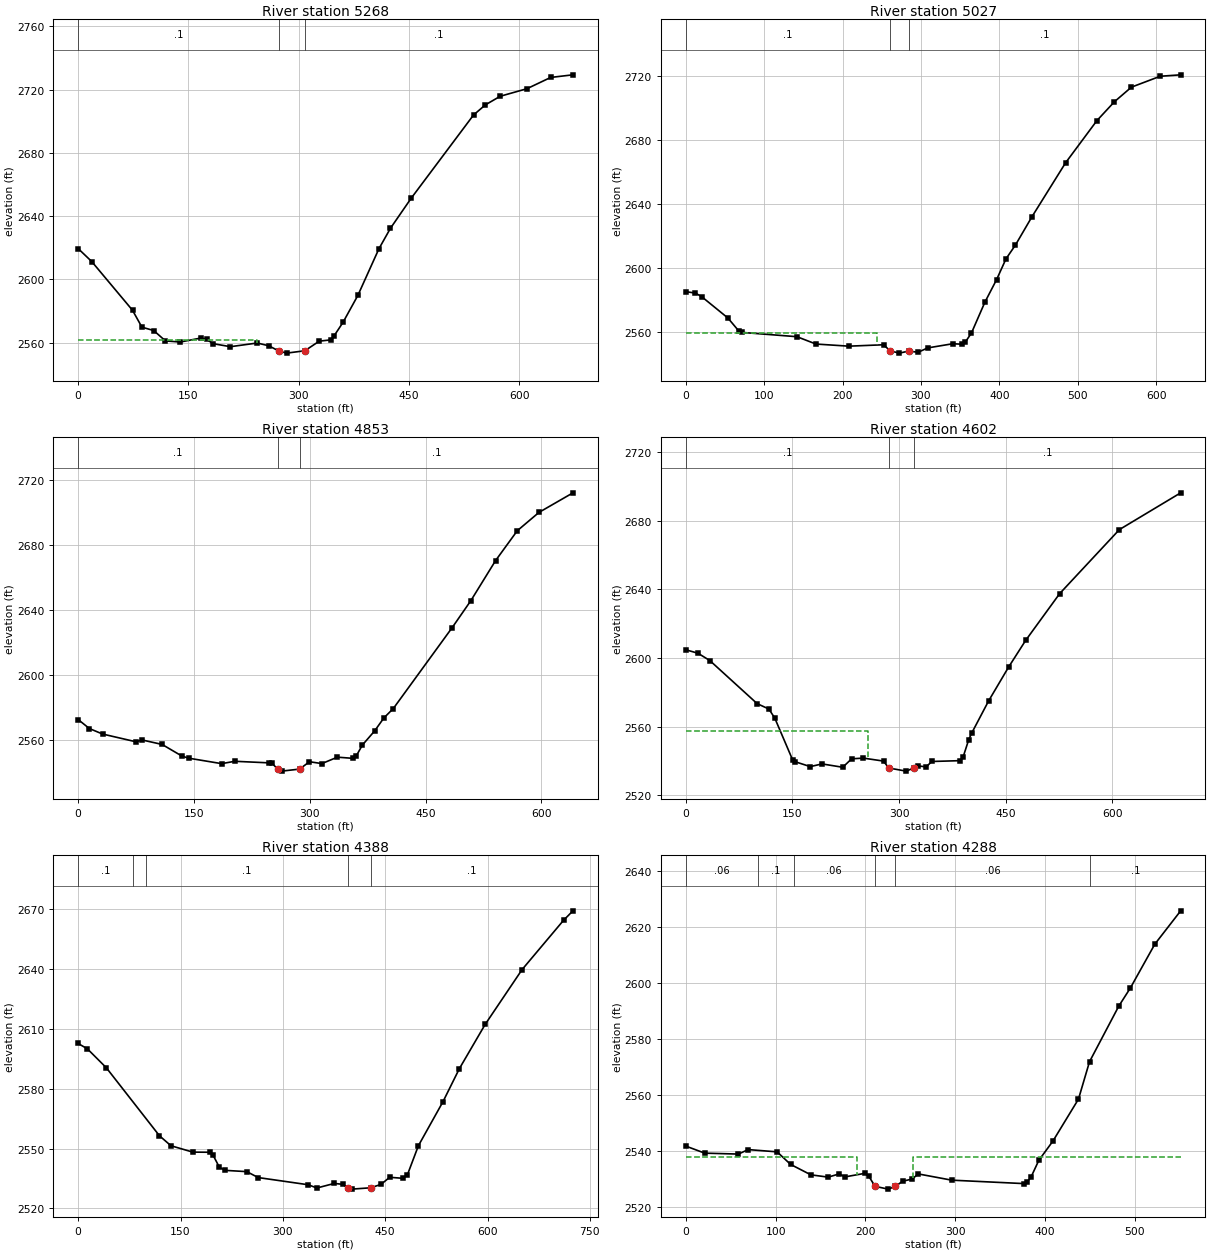
Type RM Length L Ch R = 1 ,5268    ,240.7,240.7,240.7
XS GIS Cut Line= 3
2277211.51334209 514767.600745142277229.33481233514524.634447413
2277173.09832054514099.186000202
#Sta/Elev= 30
       0 2619.49    18.5 2611.27    73.9 2580.51    86.7 2569.81   102.7  2567.7
   118.7 2561.13   138.8 2560.43   166.9 2562.94   174.9 2562.17   182.9 2559.43
     207 2557.48   243.6  2559.8   259.2 2558.05272.66962554.818   283.4 2553.41
308.26962554.907   327.8 2560.97     344 2561.82     348 2564.34   360.1 2572.83
   380.3 2589.85     409  2619.4   424.6 2632.28   452.9 2651.35   537.6  2703.9
   553.7  2710.3   573.9 2715.75   610.2 2720.51   642.5 2727.64   672.8 2729.29
#Mann= 3 ,-1,0
       0      .1       0272.6696    .045       0308.2696      .1       0
#XS Ineff= 2 , 0
          242.58 2561.57
Permanent Ineff=
       F       F
Bank Sta=272.6696,308.2696
XS Rating Curve= 0 ,0
Exp/Cntr(USF)=0,0
Exp/Cntr=0.3,0.1

Type RM Length L Ch R = 1 ,5027    ,172.4,174.4,176.4
XS GIS Cut Line= 3
2277366.22769556514715.7218207722277464.09125921514543.331863536
2277452.17234708514110.301457527
#Sta/Elev= 30
       0  2585.5    12.1 2584.62    20.1  2582.4    53.5 2569.09    67.3 2561.07
    71.9 2560.02   141.7 2557.35     166 2552.76     208 2551.43   252.4 2552.31
   260.4 2548.55   272.4 2547.08   284.4 2548.36   296.4 2547.61   308.4 2550.32
   340.4 2552.94   352.4 2552.67   356.4 2553.85   364.4 2559.64   381.6 2578.96
   396.5 2593.04   408.5 2606.03   420.5  2614.6   441.7 2632.39   484.5 2666.03
   524.5 2692.42   546.8 2704.19   568.5 2713.32   605.3 2720.15   631.4 2721.04
#Mann= 3 ,-1,0
       0      .1       0   260.4    .045       0   284.4      .1       0
#XS Ineff= 2 , 0
          243.32 2559.43
Permanent Ineff=
       F       F
Bank Sta=260.4,284.4
XS Rating Curve= 0 ,0
Exp/Cntr(USF)=0,0
Exp/Cntr=0.3,0.1

Type RM Length L Ch R = 1 ,4853    ,252.2,250.8,249
XS GIS Cut Line= 3
2277551.80107389514758.7675394582277625.50022573514565.586429313
2277665.69976311514133.441402573
#Sta/Elev= 30
       0 2572.73    14.5  2567.2    31.7  2563.8    74.5 2559.09      83 2560.15
   108.7 2557.42   134.4 2550.26     143 2548.98   185.8 2545.61   202.9 2547.06
   247.3 2546.09   251.4 2545.71  258.49 2542.17   263.4 2541.01   286.8 2542.26
   299.6 2546.79   315.6 2545.64   335.7 2549.59   355.8 2548.87   359.8 2550.05
   368.1 2557.05   383.9  2565.7     396 2573.75   408.1 2579.46   484.4 2629.25
   508.5 2645.76   540.6 2670.45   568.7  2688.8   596.8 2700.07   640.8  2712.1
#Mann= 3 ,-1,0
       0      .1       0  258.49    .045       0   286.8      .1       0
Bank Sta=258.49,286.8
XS Rating Curve= 0 ,0
Exp/Cntr(USF)=0,0
Exp/Cntr=0.3,0.1

Type RM Length L Ch R = 1 ,4602    ,213.6,213.6,213.6
XS GIS Cut Line= 3
2277809.58146853514809.6770317032277879.58939527514562.029279659
2277878.46536129514122.903886374
#Sta/Elev= 30
       0 2604.81    17.1  2602.8    33.8 2598.51   100.3 2573.45   116.9 2570.29
   125.2 2564.97   150.2 2540.73   154.3 2539.54   175.1 2536.76   191.7 2538.33
   220.8 2536.38   233.3  2541.3   249.9 2541.71   278.2 2539.98285.58432535.933
   310.2 2534.13   321.5 2536.08   326.2 2537.24   338.2 2536.58   346.2 2539.75
   386.2 2540.23   390.2 2542.28   398.2 2552.53   402.2 2556.18   426.2 2575.08
   454.2 2594.69   478.2 2610.23   526.2 2637.55   610.2 2674.82   696.5 2696.25
#Mann= 3 ,-1,0
       0      .1       0285.5843    .045       0   321.5      .1       0
#XS Ineff= 2 , 0
          255.81 2557.32
Permanent Ineff=
       F       F
Bank Sta=285.5843,321.5
XS Rating Curve= 0 ,0
Exp/Cntr(USF)=0,0
Exp/Cntr=0.3,0.1

Type RM Length L Ch R = 1 ,4388    ,100.3,100.3,100.3
BEGIN DESCRIPTION:
structure xs 4
END DESCRIPTION:
XS GIS Cut Line= 4
2277855.37204987514852.4550427592278046.71954387514630.372625016
2278115.38458749514445.6898015612278112.85728176514210.657927956
#Sta/Elev= 30
       0 2602.71    13.5 2600.04    41.3 2590.54   119.2 2556.44     136 2551.46
     168 2548.26   192.9  2548.2   197.3 2547.03   207.1 2540.58   215.7 2539.11
   247.2 2538.48   263.8 2535.51   337.1 2531.91   349.9 2530.28   375.5 2532.57
   388.3 2532.09   394.8 2530.24   401.1 2529.71   428.6 2530.38   443.8 2532.07
   456.6 2535.65   475.6 2535.14   482.2 2536.55   498.7 2551.49   534.7 2573.54
   558.7 2590.09   596.6 2612.32   650.7 2639.79   711.5  2664.5   725.2 2669.21
#Mann= 5 ,-1,0
       0      .1       0      80     .06       0     100      .1       0
   394.8    .045       0   428.6      .1       0
Bank Sta=394.8,428.6
XS Rating Curve= 0 ,0
Exp/Cntr(USF)=0,0
Exp/Cntr=0.3,0.1

Type RM Length L Ch R = 1 ,4288    ,61,61,61
BEGIN DESCRIPTION:
structure xs 3; 20.2 ft between structure and xs
END DESCRIPTION:
XS GIS Cut Line= 3
2278022.10406235514736.753714789 2278263.1955734514468.731768993
2278226.00592542514281.501127432
#Sta/Elev= 30
       0 2541.84      21 2539.33    58.6    2539    69.4  2540.6   101.7 2539.79
   116.7 2535.31   139.3 2531.59   158.6 2530.77   171.1 2531.94     177 2530.84
   199.4 2532.12   203.9 2531.07   210.8 2527.49   225.4 2526.49   233.4 2527.44
   241.5 2529.31   252.3  2530.1   258.9 2531.92   296.2 2529.69   376.3 2528.47
   380.4 2529.12   384.5 2530.69   393.3 2536.76     409 2543.62   437.5 2558.61
   449.8 2571.95   482.4 2591.78   495.4  2598.3   522.6 2613.91   551.4  2625.8
#Mann= 6 ,-1,0
       0     .06       0      80      .1       0     120     .06       0
   210.8    .045       0   233.4     .06       0   450.5      .1       0
#XS Ineff= 2 , 0
           190.6  2537.8   253.6          2537.8
Permanent Ineff=
       F       F
Bank Sta=210.8,233.4
XS Rating Curve= 0 ,0
Exp/Cntr(USF)=0,0
Exp/Cntr=0.5,0.3

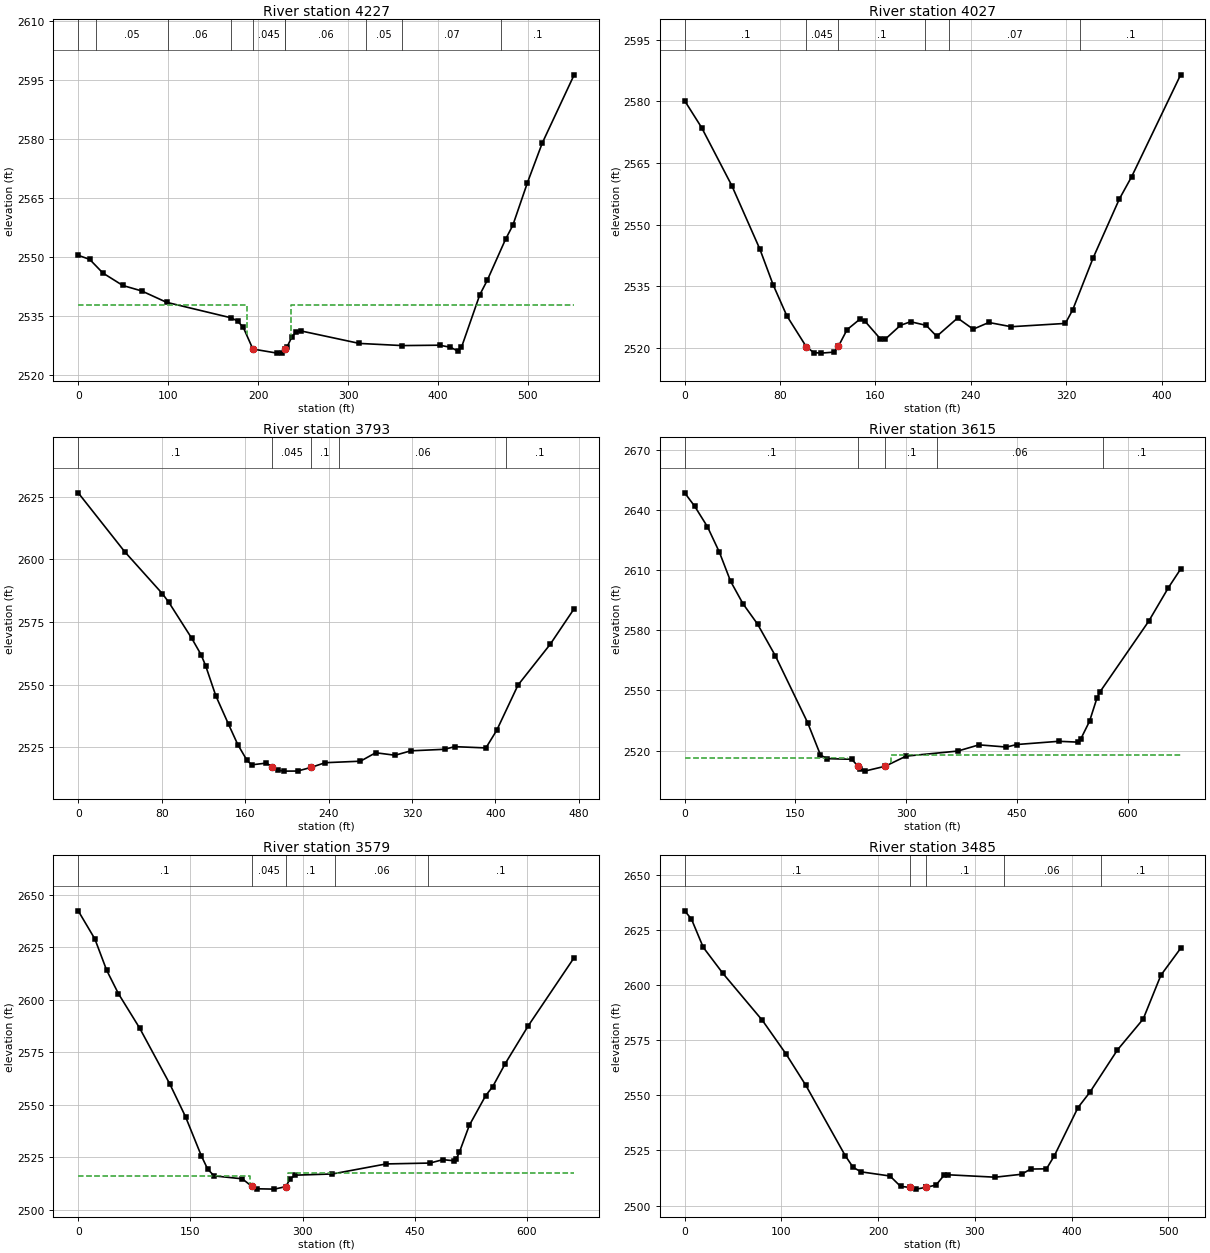
Type RM Length L Ch R = 1 ,4227    ,199.7,199.7,199.7
BEGIN DESCRIPTION:
structure xs 2; 18.9 ft between structure and xs
END DESCRIPTION:
XS GIS Cut Line= 3
 2278086.4787125514749.5818099362278327.57022355 514481.55986414
2278290.38057557514294.329222579
#Sta/Elev= 30
       0 2550.44    12.8 2549.39    27.4 2545.93    49.6 2542.75    70.5 2541.37
    98.2 2538.47     170 2534.52   177.1  2533.7   183.5  2532.1   194.2 2526.57
   221.1 2525.53   226.5 2525.66   229.8 2526.48   231.9 2526.98   237.3 2529.52
   242.2 2530.95   247.9 2531.17   312.6    2528   360.5 2527.45   401.7 2527.55
   413.9 2527.02   422.1 2526.06   426.1 2526.99   446.5  2540.4   454.7 2544.03
   475.1 2554.51   483.2 2558.07   499.5 2568.96   515.9    2579   551.4 2596.39
#Mann= 10 ,-1,0
       0     .06       0      20     .05       0     100     .06       0
     170     .05       0   194.2    .045       0   229.8     .05       0
     230     .06       0     320     .05       0   360.5     .07       0
   470.5      .1       0
#XS Ineff= 2 , 0
           187.5  2537.7   236.3          2537.8
Permanent Ineff=
       F       F
Bank Sta=194.2,229.8
XS Rating Curve= 0 ,0
Exp/Cntr(USF)=0,0
Exp/Cntr=0.5,0.3

Type RM Length L Ch R = 1 ,4027    ,234.4,234.4,234.4
BEGIN DESCRIPTION:
structure xs 1
END DESCRIPTION:
XS GIS Cut Line= 3
2278466.50766136514682.445521378 2278398.6077423514503.035166123
2278307.52248501514298.231345201
#Sta/Elev= 30
       0 2580.13    14.2 2573.61    39.5 2559.52    63.1 2544.04    74.2 2535.39
    85.7 2527.84   102.1 2520.29   108.3 2518.91   114.5 2518.78   125.4 2519.03
   128.9 2520.42   136.2 2524.48   146.8 2526.99     151 2526.61   163.9 2522.33
   168.2 2522.16     181 2525.54   189.5 2526.41   202.6 2525.53   211.4 2522.86
   228.9 2527.31     242  2524.6   255.1 2526.23   273.9  2525.2   319.3    2526
   325.4 2529.25   342.7 2541.98   364.6 2556.24     375 2561.71     416 2586.43
#Mann= 6 ,-1,0
       0      .1       0   102.1    .045       0   128.9      .1       0
  201.83     .05       0  221.83     .07       0  331.83      .1       0
Bank Sta=102.1,128.9
XS Rating Curve= 0 ,0
Exp/Cntr(USF)=0,0
Exp/Cntr=0.3,0.1

Type RM Length L Ch R = 1 ,3793    ,177.9,177.9,177.9
BEGIN DESCRIPTION:
structure xs 4
END DESCRIPTION:
XS GIS Cut Line= 2
2278759.08454839514485.3701465282278327.39563206 514286.08664423
#Sta/Elev= 30
       0  2626.5    44.5 2603.06    80.7 2586.28    86.9 2582.83   108.9 2568.46
   117.8 2561.95   122.2 2557.53   131.9  2545.6   144.2 2534.14     153 2526.11
   161.8 2519.85   166.2 2518.04   180.2 2518.72   186.2 2517.26   191.3 2515.92
   197.1 2515.53   210.3 2515.56   223.5 2517.04   236.7 2518.89   270.6 2519.49
   285.2 2522.86   303.8 2521.86   318.8 2523.62   351.3 2524.24     361 2525.29
   390.9 2524.78   401.3 2531.84   421.7 2549.86   452.6 2566.14   475.5  2580.3
#Mann= 5 ,-1,0
       0      .1       0   186.2    .045       0   223.5      .1       0
     250     .06       0     410      .1       0
Bank Sta=186.2,223.5
XS Rating Curve= 0 ,0
Exp/Cntr(USF)=0,0
Exp/Cntr=0.5,0.3

Type RM Length L Ch R = 1 ,3615    ,35.6,35.6,35.6
BEGIN DESCRIPTION:
structure xs 3; 16.8 ft between structure and xs
END DESCRIPTION:
XS GIS Cut Line= 4
2278868.48915434514278.9363241232278692.39682802514201.274442697
2278538.91192912514350.7508167772278296.53801642514243.029077796
#Sta/Elev= 30
       0 2648.48    13.7 2641.71    30.9 2631.54    47.1 2618.82    62.2  2604.4
      79 2593.17    98.7 2583.06   122.8 2567.27   166.5 2533.97     184 2517.77
   192.8 2515.97   226.3 2515.65     235 2512.13   237.4 2510.64   243.9 2509.74
   271.7 2512.18     300 2517.22   370.1 2519.75   398.7 2522.84     436 2521.74
     450 2523.01   506.9 2524.61   532.3  2524.2   536.6 2525.74   548.5  2534.6
   558.5  2546.1   562.9 2549.38   628.6 2584.43   655.4 2601.23   671.9 2610.47
#Mann= 5 ,-1,0
       0      .1       0     235    .045       0   271.7      .1       0
  342.46     .06       0   566.7      .1       0
#XS Ineff= 2 , 0
           219.5  2516.2     280          2517.7
Permanent Ineff=
       F       F
Bank Sta=235,271.7
XS Rating Curve= 0 ,0
Exp/Cntr(USF)=0,0
Exp/Cntr=0.5,0.3

Type RM Length L Ch R = 1 ,3579    ,94.4,94.4,94.4
BEGIN DESCRIPTION:
structure xs 2; 10.6 ft between structure and xs
END DESCRIPTION:
XS GIS Cut Line= 4
2278880.03076923514229.5638604242278687.04626793514163.825867224
2278550.45354401514301.3783530772278308.07963131514193.656614097
#Sta/Elev= 30
       0 2642.28    22.3 2628.88      38 2614.05    53.8 2602.86    82.1 2586.54
   122.4 2559.99   143.5 2544.35   164.7  2525.7   173.1 2519.45   181.6 2516.25
   219.3 2514.85   232.3 2511.22   239.6 2510.11   262.2 2509.95   277.6 2511.15
   283.2 2514.83   290.3 2516.59   339.8 2517.16   411.7 2521.93   470.3 2522.35
   487.5 2523.96   502.6 2523.42   505.7 2524.46   509.7 2527.61   522.8 2540.25
   544.7 2554.39   554.2 2558.73   570.9 2569.66   601.6 2587.59     663 2620.03
#Mann= 5 ,-1,0
       0      .1       0   232.3    .045       0   277.6      .1       0
  343.87     .06       0  467.72      .1       0
#XS Ineff= 2 , 0
             229  2516.2     281          2517.7
Permanent Ineff=
       F       F
Bank Sta=232.3,277.6
XS Rating Curve= 0 ,0
Exp/Cntr(USF)=0,0
Exp/Cntr=0.5,0.3

Type RM Length L Ch R = 1 ,3485    ,293,293,293
BEGIN DESCRIPTION:
structure xs 1
END DESCRIPTION:
XS GIS Cut Line= 2
 2278907.0290875514164.0876026562278404.12806092514063.617803713
#Sta/Elev= 30
       0 2633.64       7  2629.9    19.2 2617.09    39.6 2605.24    80.4 2583.94
   104.9 2568.67   125.3 2554.51   166.1 2522.58   174.2 2517.33   182.4  2515.3
   212.3 2513.42   223.2 2508.72   232.7 2508.26   239.4 2507.47   249.7  2508.3
   249.7 2508.31   259.9 2509.31     268 2513.66   272.1 2513.98   321.1 2512.88
   348.3 2514.21   357.8 2516.57   374.1 2516.67   382.3 2522.65   406.7 2544.45
     419 2551.41   447.5 2570.59   474.1 2584.58   492.4 2604.45   512.8 2616.63
#Mann= 5 ,-1,0
       0      .1       0   232.7    .045       0   249.7      .1       0
     330     .06       0     430      .1       0
Bank Sta=232.7,249.7
XS Rating Curve= 0 ,0
Exp/Cntr(USF)=0,0
Exp/Cntr=0.3,0.1

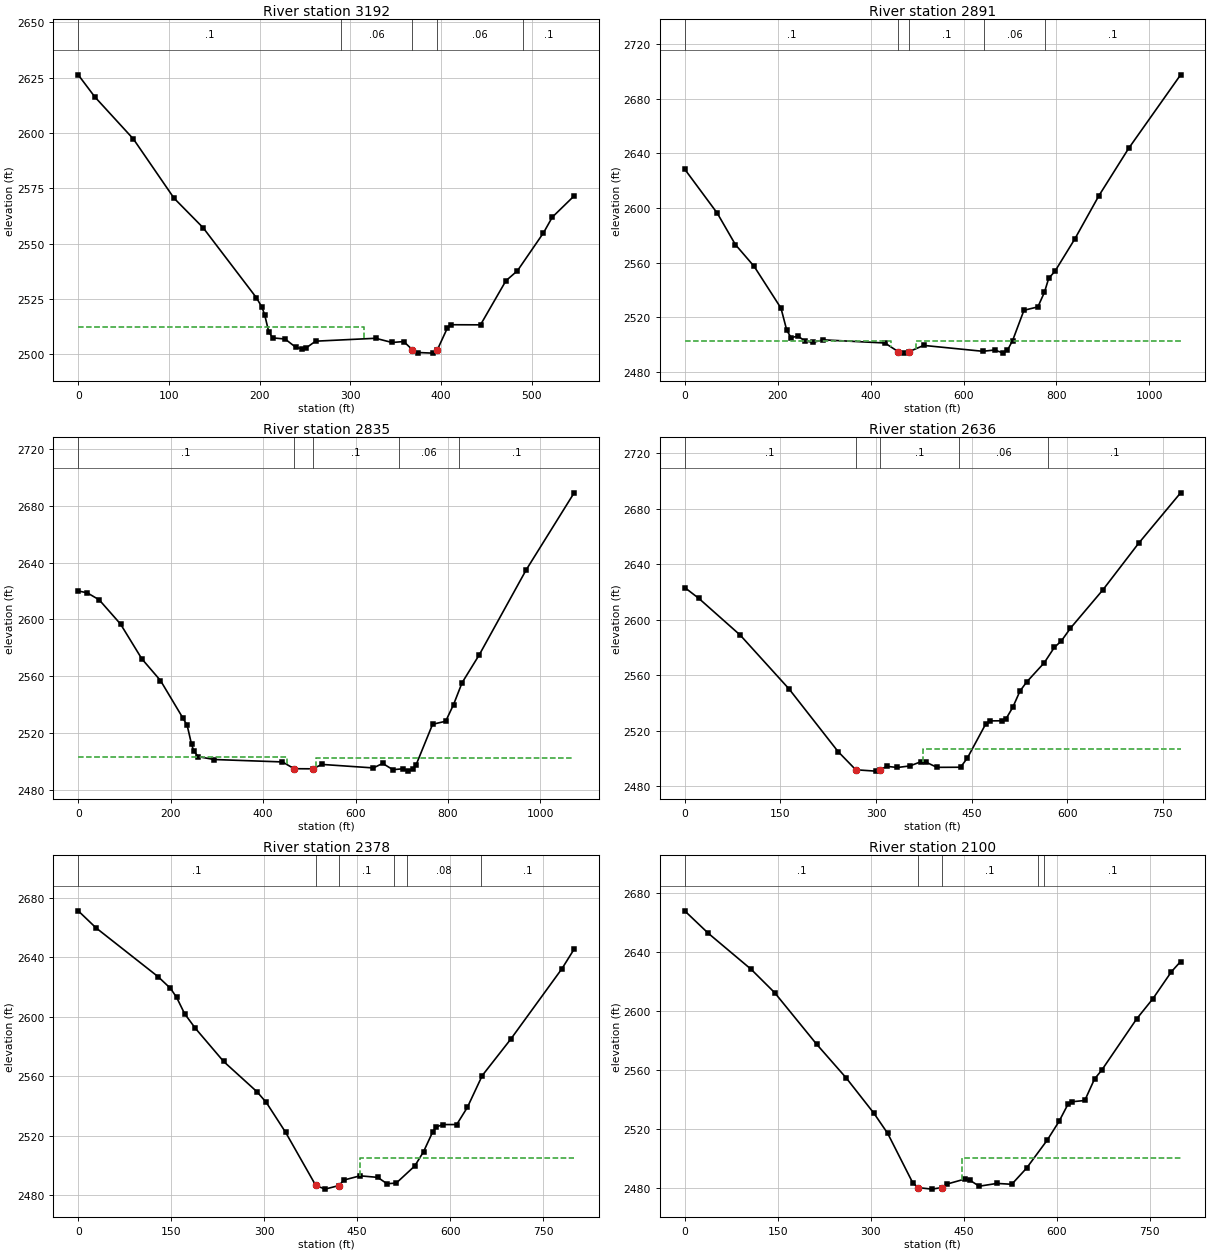
Type RM Length L Ch R = 1 ,3192    ,301.1,301.1,301.1
BEGIN DESCRIPTION:
structure xs 4
END DESCRIPTION:
XS GIS Cut Line= 4
2279037.44228494513993.7949650032278725.12810217513827.636324162
 2278658.6484004513823.4813428012278534.83039965513847.475605901
#Sta/Elev= 30
       0 2626.29    18.3 2616.32    60.9 2597.24   105.6 2570.54   137.6 2557.22
   196.3 2525.61   202.5 2521.28   205.5 2517.79   209.9 2510.27   214.2 2507.44
     228 2506.91   239.8 2503.15   246.1 2502.56   250.6 2502.73   261.6 2505.94
   327.7 2507.25   345.8 2505.35   358.7 2505.77   368.3 2502.06   374.8 2500.81
   390.6 2500.54  395.74 2502.04   406.8  2511.9   410.8 2513.37   443.3 2513.32
   471.3 2533.23     484 2537.76   512.7 2554.89   522.4 2561.97   546.5 2571.59
#Mann= 5 ,-1,0
       0      .1       0     290     .06       0   368.3    .045       0
  395.74     .06       0  490.37      .1       0
#XS Ineff= 2 , 0
          315.38 2512.53
Permanent Ineff=
       F       F
Bank Sta=368.3,395.74
XS Rating Curve= 0 ,0
Exp/Cntr(USF)=0,0
Exp/Cntr=0.5,0.3

Type RM Length L Ch R = 1 ,2891    ,55.5,55.5,55.5
BEGIN DESCRIPTION:
structure xs 3; 16 ft between structure and xs
END DESCRIPTION:
XS GIS Cut Line= 6
 2279054.9715744513988.0934942442278837.13854734513842.885693361
 2278906.8381694513662.6725880862278908.59840358513623.654063548
2278971.87485498513488.4078229222278667.91270361513195.161075457
#Sta/Elev= 30
       0 2628.55    70.2 2596.24   109.1 2573.28   149.5  2557.3   207.2 2526.73
   219.7 2510.45   229.1 2505.04   243.7 2506.33   258.1  2502.7   276.5 2501.66
   297.9 2503.52   430.9 2501.19   459.4 2494.87     472 2493.78  482.45 2494.82
   514.3 2499.43   641.3 2495.13   666.7 2496.06   683.9 2494.06   694.3 2495.83
   705.5  2502.9     730 2525.17     760 2527.64   774.1 2538.39   783.3 2548.61
   796.7 2553.72   839.5 2577.44   891.3  2609.1   955.1 2643.66  1067.1 2697.62
#Mann= 5 ,-1,0
       0      .1       0   459.4    .045       0  482.45      .1       0
  644.61     .06       0  774.73      .1       0
#XS Ineff= 2 , 0
           443.4    2503  498.45          2502.6
Permanent Ineff=
       F       F
Bank Sta=459.4,482.45
XS Rating Curve= 0 ,0
Exp/Cntr(USF)=0,0
Exp/Cntr=0.5,0.3

Type RM Length L Ch R = 1 ,2835    ,199.4,199.4,199.4
BEGIN DESCRIPTION:
structure xs 2; 22.9 ft between structure and xs
END DESCRIPTION:
XS GIS Cut Line= 6
2279092.27152902513983.9759376892278876.09459755 513839.87220053
2278942.04285319 513664.726194642278957.29821617513658.565374977
2279014.69512822513488.1544894032278705.21265823513191.043518902
#Sta/Elev= 30
       0    2620    19.3 2618.75    45.4 2613.77    91.5 2596.74   137.7  2572.2
     178 2556.96   227.1 2530.23   235.7 2525.44   245.3 2511.98   250.2 2507.22
   259.7 2503.35   294.1 2501.35     442 2499.64   467.2 2494.87   507.9 2494.79
     527  2497.9   638.7 2495.42   658.7 2498.61   680.9 2494.19   701.8  2494.8
   713.1 2493.17   724.4 2494.58   730.8 2497.35   766.8 2526.15   795.1 2528.29
   812.1 2539.98   830.6 2555.42   867.9 2575.12   969.2 2634.81  1073.1 2689.11
#Mann= 5 ,-1,0
       0      .1       0   467.2    .045       0   507.9      .1       0
  694.13     .06       0  824.13      .1       0
#XS Ineff= 2 , 0
             452    2503     515          2502.6
Permanent Ineff=
       F       F
Bank Sta=467.2,507.9
XS Rating Curve= 0 ,0
Exp/Cntr(USF)=0,0
Exp/Cntr=0.5,0.3

Type RM Length L Ch R = 1 ,2636    ,258.2,258.2,258.2
BEGIN DESCRIPTION:
structure xs 1
END DESCRIPTION:
XS GIS Cut Line= 2
2279295.73010825513696.8289040122278728.02326712 513165.24266622
#Sta/Elev= 30
       0 2623.13    22.1 2615.32    87.1 2588.82   163.6 2550.07   240.5 2504.94
   268.3  2491.8   299.4 2490.83   306.3  2491.9   317.2 2494.24   333.7 2493.46
   353.2 2494.58   370.2 2497.55   378.7 2497.23   395.6 2493.55   432.6 2493.63
   443.3 2500.27     472 2524.73   479.4 2527.02   498.1 2527.11   503.5 2528.22
   514.5  2536.8   525.8 2548.52   536.4 2555.11   563.8 2568.87   579.6 2579.91
   590.6 2584.58     605 2593.84     656 2621.54   711.8 2654.96   777.7 2691.34
#Mann= 5 ,-1,0
       0      .1       0   268.3    .045       0   306.3      .1       0
     430     .06       0     570      .1       0
#XS Ineff= 2 , 0
                          373.63         2507.04
Permanent Ineff=
       F       F
Bank Sta=268.3,306.3
XS Rating Curve= 0 ,0
Exp/Cntr(USF)=0,0
Exp/Cntr=0.3,0.1

Type RM Length L Ch R = 1 ,2378    ,277.7,277.7,277.7
XS GIS Cut Line= 2
2279485.19300585513624.366737496 2279006.8838823512983.102063329
#Sta/Elev= 30
       0 2671.16    28.7 2659.71   128.8 2626.88   148.8 2619.03   158.7 2612.97
   171.6 2601.99     189 2592.14   234.5 2569.87   288.4 2549.47   303.4 2542.29
   334.6 2522.15   383.2 2486.47   398.2 2483.99   420.3 2486.38   428.9 2490.13
   454.6 2492.94   483.2 2491.89     498 2487.64     513 2488.04   542.9 2499.57
     557 2509.11   571.8 2522.46   577.5 2525.69   587.8 2527.41   610.5 2527.42
   627.7 2538.95   651.8  2560.4   697.6 2584.78   780.4  2632.3     800 2645.42
#Mann= 6 ,-1,0
       0      .1       0   383.2    .045       0   420.3      .1       0
     510     .06       0     530     .08       0     650      .1       0
#XS Ineff= 2 , 0
                          455.21         2505.13
Permanent Ineff=
       F       F
Bank Sta=383.2,420.3
XS Rating Curve= 0 ,0
Exp/Cntr(USF)=0,0
Exp/Cntr=0.3,0.1

Type RM Length L Ch R = 1 ,2100    ,300,300,300
XS GIS Cut Line= 2
2279690.62721875513479.5656445642279254.68391457512808.779959311
#Sta/Elev= 30
       0 2667.67    38.2 2652.44   107.3  2628.1   145.2 2612.31   212.7 2577.56
   260.5 2554.72   305.5 2530.67   327.5 2517.18   367.8 2483.87   376.5 2480.53
   398.8 2479.52   415.6 2480.62   422.8  2482.9   451.7  2486.3   459.6 2485.65
   475.1 2481.49   503.8 2483.38   527.6 2482.79   551.5 2493.71   584.9  2512.7
   603.9 2525.31   618.2 2536.85   625.1 2538.61   645.4 2539.44   661.2 2554.05
   672.5 2559.81   729.2 2594.68   755.3 2608.26   785.2 2626.53     800 2633.39
#Mann= 5 ,-1,0
       0      .1       0   376.5    .045       0   415.6      .1       0
     570     .06       0     580      .1       0
#XS Ineff= 2 , 0
                             448         2500.76
Permanent Ineff=
       F       F
Bank Sta=376.5,415.6
XS Rating Curve= 0 ,0
Exp/Cntr(USF)=0,0
Exp/Cntr=0.3,0.1

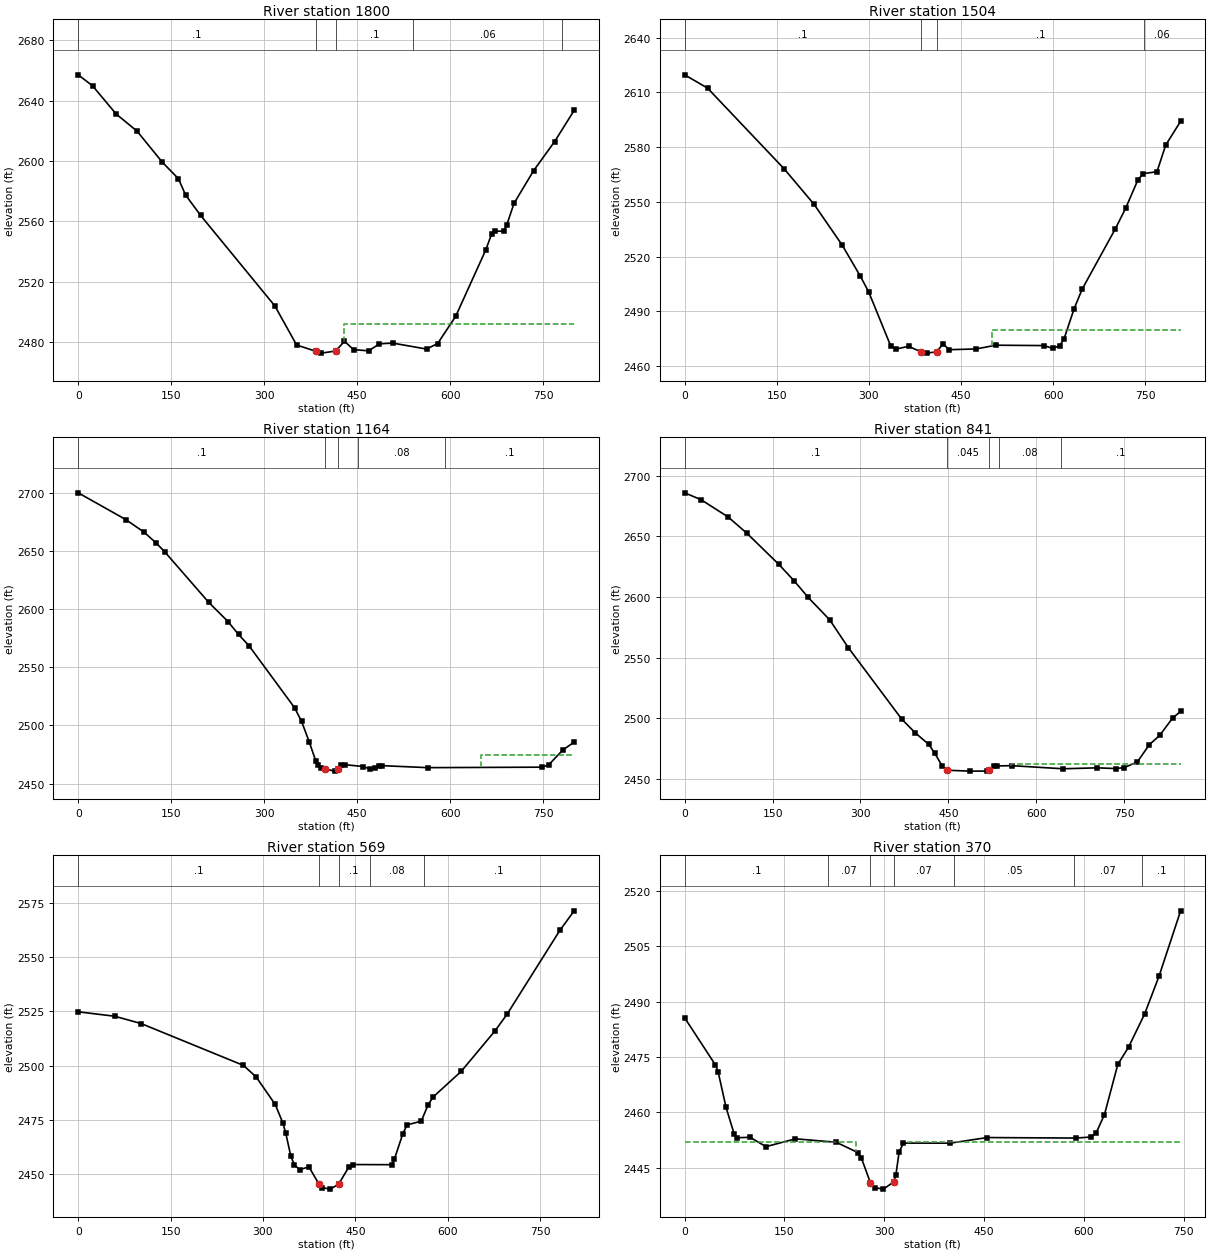
Type RM Length L Ch R = 1 ,1800    ,295.9,295.9,295.9
XS GIS Cut Line= 2
2279969.61256289513348.4486128832279519.44246572512687.126540356
#Sta/Elev= 30
       0 2657.23    23.3 2649.88      61 2631.33      95 2619.84   135.8 2599.23
   161.7 2588.33   173.2 2577.53   197.5 2563.97   317.2 2503.99   352.3 2478.08
   383.4 2473.91   392.1 2472.69   415.3 2474.09   429.5 2480.56   444.3 2474.98
   468.5 2474.22   485.9 2478.86   507.3 2479.34   561.9 2475.39   579.8 2479.05
   608.8 2497.02   657.2  2540.9   666.9 2551.74   671.7 2553.57   686.2 2553.52
   691.1 2557.46     703 2572.02   734.7 2593.74   768.5 2612.98     800 2633.66
#Mann= 5 ,-1,0
       0      .1       0   383.4    .045       0   415.3      .1       0
     540     .06       0     780      .1       0
#XS Ineff= 2 , 0
                          428.17         2492.03
Permanent Ineff=
       F       F
Bank Sta=383.4,415.3
XS Rating Curve= 0 ,0
Exp/Cntr(USF)=0,0
Exp/Cntr=0.3,0.1

Type RM Length L Ch R = 1 ,1504    ,339.7,339.7,339.7
XS GIS Cut Line= 4
2280238.50241188 513191.35828915 2280054.1788477512974.850928946
2279966.92423913512802.419202479 2279725.1506659512577.786789729
#Sta/Elev= 30
       0 2619.62    37.2 2612.35   162.1 2568.08   210.7 2548.69   256.6 2526.29
   286.2 2509.24   299.7 2500.67   335.5 2471.12   343.6 2469.36   364.5  2470.9
   384.8 2467.92   395.1 2467.18   410.6 2467.94   420.7 2472.34   430.5 2469.06
   474.6 2469.47   506.6 2471.52   585.2 2471.31   599.3 2469.78   610.6 2471.22
   617.8    2475   634.2 2491.52   647.4 2502.31   701.2  2535.2   718.2 2546.62
     738 2562.04   746.5 2565.49   769.1 2566.54   783.3 2581.14   807.6 2594.16
#Mann= 4 ,-1,0
       0      .1       0   384.8    .045       0   410.6      .1       0
  747.59     .06       0
#XS Ineff= 2 , 0
                             500            2480
Permanent Ineff=
       F       F
Bank Sta=384.8,410.6
XS Rating Curve= 0 ,0
Exp/Cntr(USF)=0,0
Exp/Cntr=0.3,0.1

Type RM Length L Ch R = 1 ,1164    ,323.6,323.6,323.6
XS GIS Cut Line= 4
2280587.58256666513019.5196996092280333.10588875512766.038586511
2280279.09113106512718.2563008642280015.32124866512460.487514558
#Sta/Elev= 30
       0 2700.07      77    2677   105.9 2666.35   125.7    2657   140.3  2648.9
   210.5  2605.9   241.7 2589.34   258.6 2578.25   275.4 2568.66   349.2 2515.13
   360.4 2503.42   372.6 2486.01   383.1 2469.74   387.1 2465.99   391.6 2463.66
 398.4422462.565   413.8 2460.73418.71722462.656   424.5  2465.7   429.9 2466.31
   459.6 2464.68   470.9 2462.56   479.4 2463.16     485 2465.03   490.1 2465.44
     564 2463.72   748.6 2464.14   759.1 2466.18   781.9 2478.95   800.1 2485.69
#Mann= 5 ,-1,0
       0      .1       0 398.442    .045       0418.7172      .1       0
   451.3     .08       0   591.3      .1       0
#XS Ineff= 2 , 0
                             650            2475
Permanent Ineff=
       F       F
Bank Sta=398.442,418.7172
XS Rating Curve= 0 ,0
Exp/Cntr(USF)=0,0
Exp/Cntr=0.3,0.1

Type RM Length L Ch R = 1 ,841     ,271.8,271.8,271.8
XS GIS Cut Line= 4
2280669.11735793512826.2986978162280469.67698377512460.671985564
2280341.91130693512416.0059359372280076.03292857512289.408709402
#Sta/Elev= 30
       0 2685.95    28.1 2680.24    74.2 2666.01   106.1 2652.64   160.7 2626.93
   187.3 2613.08   210.8 2599.65   247.3 2581.29   279.2 2558.28   370.3 2499.34
   393.6 2487.91   416.5 2478.49   426.6 2471.24   439.3 2460.79   447.7 2457.14
   487.7 2456.41   515.5 2456.46   519.8 2457.11   527.2 2460.26   532.5 2460.69
   558.2 2460.91   645.3 2458.36   704.4 2459.12   735.6 2458.53   750.3 2459.38
   772.4 2463.95     793 2478.28   810.7 2485.93   832.9  2500.4   846.3  2505.6
#Mann= 5 ,-1,0
       0      .1       0   447.7    .045       0   519.8      .1       0
  536.48     .08       0  641.83      .1       0
#XS Ineff= 2 , 0
                          557.42         2462.41
Permanent Ineff=
       F       F
Bank Sta=447.7,519.8
XS Rating Curve= 0 ,0
Exp/Cntr(USF)=0,0
Exp/Cntr=0.3,0.1

Type RM Length L Ch R = 1 ,569     ,198.9,198.9,198.9
BEGIN DESCRIPTION:
structure xs 4
END DESCRIPTION:
XS GIS Cut Line= 4
2280809.88994936512467.988308025 2280561.0865737512216.566830625
2280404.23602734512132.428458072  2280185.596237511967.731013511
#Sta/Elev= 30
       0 2524.79    59.3 2522.75   102.2 2519.37   268.4 2500.06   288.9 2494.77
     320 2482.04   332.3 2473.54     337 2468.86   345.4 2458.06   351.1 2454.18
   359.8 2451.98   374.6 2453.28   391.1 2445.28   395.6 2443.72   409.2    2443
   422.8 2445.24   439.6 2453.23   445.5 2454.34   509.1 2454.27   513.5 2456.85
   527.2 2468.59   534.1 2472.62   557.1 2474.35   568.3 2481.96   576.4 2485.51
   621.9 2497.29   676.9    2516   696.7 2523.78   782.2 2562.36   805.4 2571.37
#Mann= 5 ,-1,0
       0      .1       0   391.1    .045       0   422.8      .1       0
  473.72     .08       0  561.71      .1       0
Bank Sta=391.1,422.8
XS Rating Curve= 0 ,0
Exp/Cntr(USF)=0,0
Exp/Cntr=0.5,0.3

Type RM Length L Ch R = 1 ,370     ,66.2,66.2,66.2
BEGIN DESCRIPTION:
structure xs 3; 22 ft between structure and xs
END DESCRIPTION:
XS GIS Cut Line= 4
2280703.39468531512287.2015137572280711.70464803512171.900780998
2280459.28953037511773.022570375  2280302.438984511791.719986498
#Sta/Elev= 30
       0 2485.61    46.1 2472.91    50.2 2471.09    62.2 2461.38    74.2  2454.3
    78.2 2453.16    98.3 2453.29   122.2 2450.75   166.5 2452.88   227.7 2451.95
   260.8 2449.12   265.6 2447.71   279.3 2440.95   285.4 2439.67   298.7 2439.26
   314.4 2441.22   317.6 2443.18   322.4 2449.33   328.9 2451.72     399  2451.7
   454.9 2453.22   587.6 2453.08   610.9 2453.36   618.5 2454.43   631.1 2459.43
   651.2 2473.04   667.3 2477.67   691.4 2486.63     713 2496.81   745.6 2514.58
#Mann= 7 ,-1,0
       0      .1       0   215.6     .07       0   279.3    .045       0
   314.4     .07       0   405.6     .05       0   585.6     .07       0
  687.63      .1       0
#XS Ineff= 2 , 0
           257.3    2452   336.4          2452.1
Permanent Ineff=
       F       F
Bank Sta=279.3,314.4
XS Rating Curve= 0 ,0
Exp/Cntr(USF)=0,0
Exp/Cntr=0.5,0.3

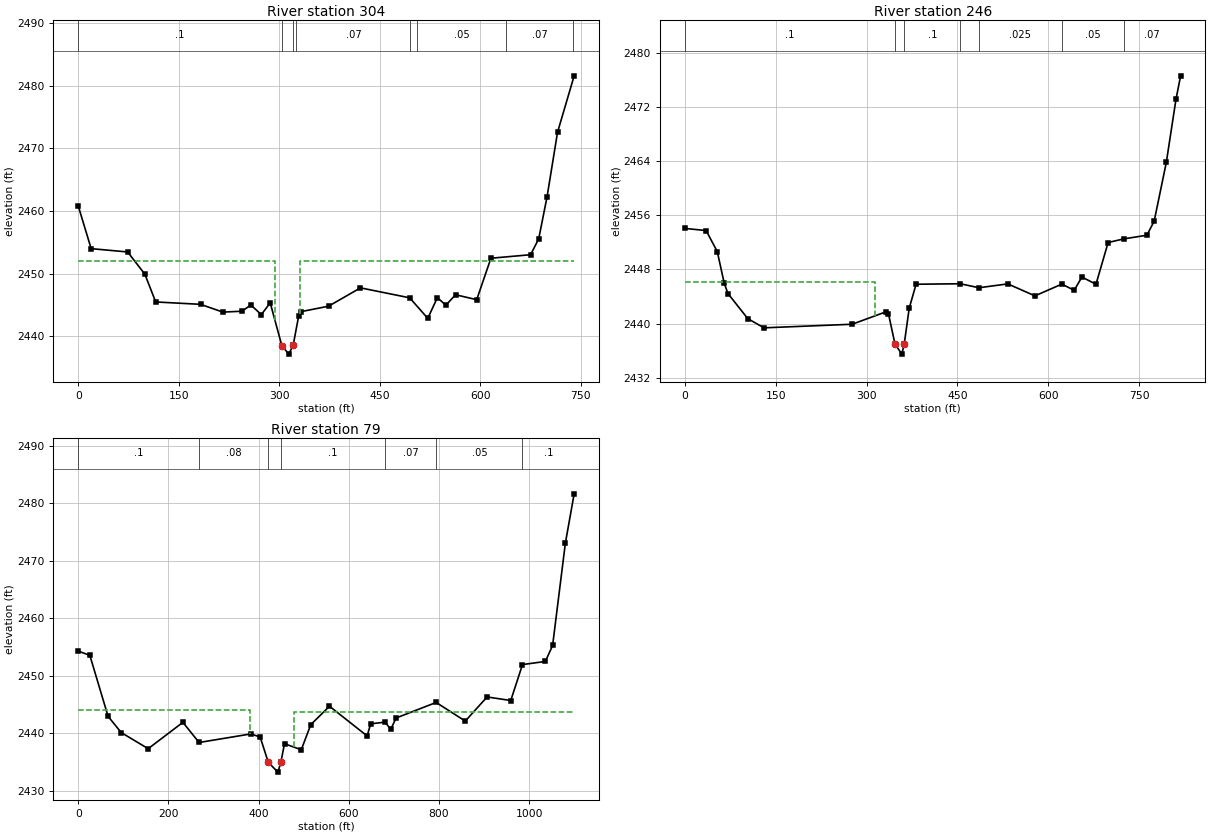
Type RM Length L Ch R = 1 ,304     ,57,58.1,59
BEGIN DESCRIPTION:
structure xs 2; 29.9 ft between structure and xs
END DESCRIPTION:
XS GIS Cut Line= 4
2280760.52567902512252.4035448612280768.83564174512137.102812103
2280510.36256125511741.2535828912280359.56997771511756.922017602
#Sta/Elev= 30
       0 2460.83    19.3    2454    73.8 2453.47    99.5 2449.91   115.6 2445.49
   182.5 2445.11   215.8 2443.87   244.5 2444.01   257.6 2445.01   273.2 2443.46
   286.5 2445.35   303.9 2438.48   314.3 2437.16   320.9 2438.66     329 2443.28
   332.8 2443.95   373.5 2444.81   421.2 2447.74   494.6 2446.15   521.6 2442.87
   535.9 2446.19   548.5 2444.97   563.1 2446.64   594.6 2445.85   615.8 2452.47
     675 2453.03   687.1 2455.56   699.6 2462.29   715.2 2472.58     740 2481.59
#Mann= 8 ,-1,0
       0      .1       0   303.9    .045       0   320.9      .1       0
   325.6     .07       0   495.6    .025       0   505.6     .05       0
  638.36     .07       0  738.36      .1       0
#XS Ineff= 2 , 0
           293.9    2452   330.9          2452.1
Permanent Ineff=
       F       F
Bank Sta=303.9,320.9
XS Rating Curve= 0 ,0
Exp/Cntr(USF)=0,0
Exp/Cntr=0.5,0.3

Type RM Length L Ch R = 1 ,246     ,162.8,166.5,168.4
BEGIN DESCRIPTION:
structure xs 1
END DESCRIPTION:
XS GIS Cut Line= 4
2280780.60576665512254.1516196432280821.81029245512148.627834044
2280596.69288317511737.5875644232280360.52060112511733.567610686
#Sta/Elev= 30
       0 2454.07    35.4 2453.75    53.8 2450.63    65.3 2445.93    71.4 2444.43
   104.1 2440.72   130.9 2439.36   276.2 2439.89   332.1 2441.73   336.1 2441.47
   346.9 2436.97   358.2 2435.47  362.19 2436.98   370.4 2442.26   381.7 2445.81
   454.7 2445.88   485.4 2445.29     533 2445.86   577.8 2444.09   622.2 2445.83
   642.5 2444.91   655.3 2446.87   678.5 2445.81   698.5 2451.98   724.5 2452.52
   762.5 2453.06   774.5 2455.15   794.5 2463.83   810.5 2473.19   818.1 2476.64
#Mann= 7 ,-1,0
       0      .1       0   346.9    .045       0  362.19      .1       0
   454.7     .07       0   485.4    .025       0   622.2     .05       0
   724.5     .07       0
#XS Ineff= 2 , 0
           313.8 2446.16
Permanent Ineff=
       F       F
Bank Sta=346.9,362.19
XS Rating Curve= 0 ,0
Exp/Cntr(USF)=0,0
Exp/Cntr=0.3,0.1

Type RM Length L Ch R = 1 ,79      ,,,
XS GIS Cut Line= 4
2280804.27451651512270.4953724512280898.17294028512020.604405967
2280795.94481763511660.9128633012280340.84036048511722.249736893
#Sta/Elev= 30
       0  2454.3    25.8 2453.55    66.2 2442.94    95.4 2440.11   155.2  2437.3
   232.2 2441.89   268.1 2438.38   382.8 2439.87   403.6 2439.34  421.66 2434.91
     443 2433.22   449.4  2434.9   457.6 2438.17   494.8 2437.11   515.9 2441.49
   557.4 2444.69   640.9 2439.52   648.7 2441.63     681 2441.93   693.1 2440.65
   705.2 2442.65     794 2445.35   858.6 2442.11     907 2446.31   959.5 2445.69
   985.5 2451.95  1036.2 2452.49  1052.3 2455.27  1080.6 2473.08  1100.1 2481.68
#Mann= 7 ,-1,0
       0      .1       0   268.1     .08       0  421.66    .045       0
   449.4      .1       0     681     .07       0     794     .05       0
   985.5      .1       0
#XS Ineff= 2 , 0
          380.03 2443.98  479.01         2443.61
Permanent Ineff=
       F       F
Bank Sta=421.66,449.4
XS Rating Curve= 0 ,0
Exp/Cntr(USF)=0,0
Exp/Cntr=0.3,0.1
LCMann Table=0

Chan Stop Cuts=-1
Use User Specified Reach Order=0
Composite Channel Slope=5